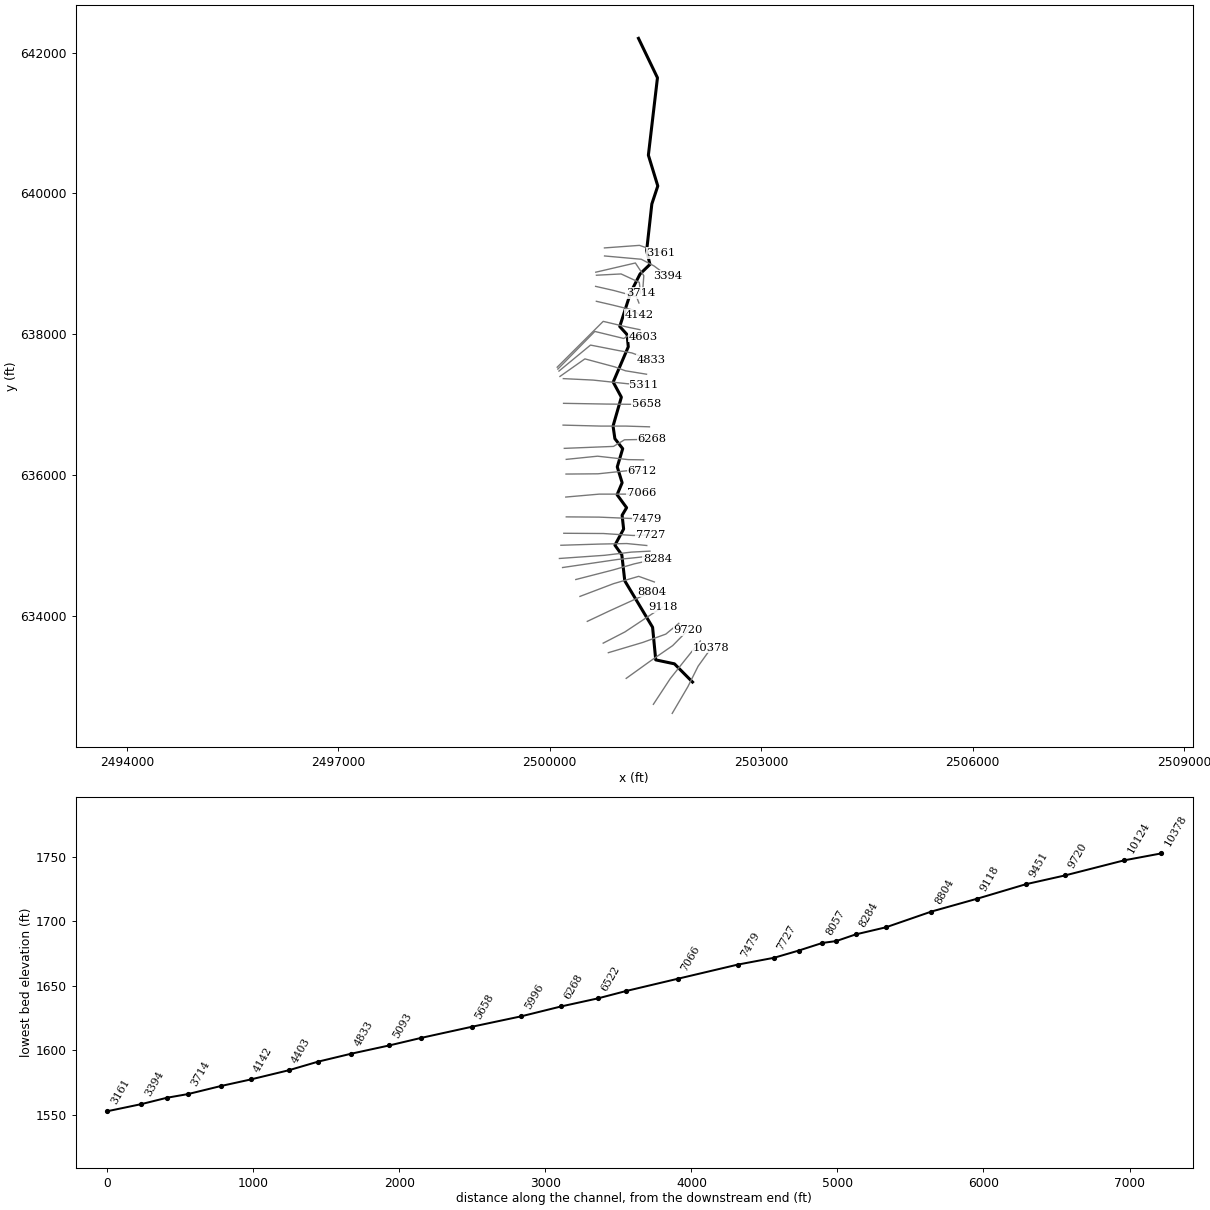
--- BUCKLICKRN.prj (project) ---

Proj Title=BUCKLICKRN
Current Plan=p01
Default Exp/Contr=0,0
English Units
Geom File=g01
Flow File=f01
Plan File=p01
BEGIN DESCRIPTION:
Stream Name: Buck Lick Run
Flood Zone: Zone A
Pendleton County, WV
WVDHSEM Flood Warning & Analysis Mapping
HEC-RAS Version: 5.0.7
Hydrology Method:
Regression was used
Model Notes:
Model ties in with Kettle Creek
END DESCRIPTION:
DSS File=dss
DSS Export Rating Curves= 0
DSS Export Rating Curve Sorted= 0
DSS Export Volume Flow Curves= 0
DXF OffsetX= 0
DXF OffsetY= 0
DXF ScaleX= 0
DXF ScaleY= 0

--- BUCKLICKRN.p01 (plan) ---

Plan Title=Floodplain
Program Version=5.07
Short Identifier=Floodplain
Geom File=g01
Flow File=f01
Subcritical Flow
K Sum by GR= 0
Std Step Tol= 0.01
Critical Tol= 0.01
Num of Std Step Trials= 20
Max Error Tol= 0.3
Flow Tol Ratio= 0.001
Split Flow NTrial= 30
Split Flow Tol= 0.02
Split Flow Ratio= 0.02
Log Output Level= 0
Friction Slope Method= 1
Unsteady Friction Slope Method= 2
Unsteady Bridges Friction Slope Method= 1
Parabolic Critical Depth
Global Vel Dist= 0 , 0 , 0
Global Log Level= 0
CheckData=True
Encroach Param=-1 ,0,0, 0
Computation Interval=0.1SEC
Output Interval=1MIN
Instantaneous Interval=Max Profile
Mapping Interval=1HOUR
Computation Time Step Use Courant=        0
Computation Time Step Use Time Series=    0
Computation Time Step Count To Double=0
Computation Time Step Max Doubling=0
Computation Time Step Max Halving=0
Computation Time Step Residence Courant=0
Run HTab= 0
Run UNet= 0
Run Sediment= 0
Run PostProcess= 0
Run WQNet= 0
Run RASMapper= 0
UNET Theta= 0
UNET Theta Warmup= 0
UNET ZTol= 0
UNET ZSATol= 0
UNET MxIter= 0
UNET Max Iter WO Improvement= 0
UNET MaxInSteps= 0
UNET DtIC= 0
UNET DtMin= 0
UNET MaxCRTS= 0
UNET WFStab= 0
UNET SFStab= 0
UNET WFX= 1
UNET SFX= 1
UNET 1D Methodology=Finite Difference
UNET DSS MLevel= 1
UNET Pardiso=0
UNET DZMax Abort= 0
UNET Use Existing IB Tables= 0
UNET Froude Reduction=False
UNET Froude Limit= 0
UNET Froude Power= 0
UNET D1 Cores= 0
UNET D2 Coriolis=0
UNET D2 Cores= 0
UNET D2 Theta= 1
UNET D2 Theta Warmup= 1
UNET D2 Z Tol= 0.01
UNET D2 Volume Tol= 0.01
UNET D2 Max Iterations= 20
UNET D2 Equation= 0
UNET D2 RampUpFraction=0.1
UNET D2 TimeSlices= 1
UNET D2 BCVolumeCheck=0
UNET D1D2 MaxIter= 0
UNET D1D2 ZTol=0.01
UNET D1D2 QTol=0.1
UNET D1D2 MinQTol=1
DSS File=dss
Write IC File= 0
Write IC File at Fixed DateTime=0
Write IC File at Sim End=0
Echo Input=False
Echo Parameters=False
Echo Output=False
Write Detailed= 0
HDF Write Warmup=0
HDF Write Time Slices=0
HDF Flush=0
HDF Face Node Velocities=0
HDF Compression= 1
HDF Chunk Size= 1
HDF Spatial Parts= 1
HDF Use Max Rows=0
HDF Fixed Rows= 1
Calibration Method= 0
Calibration Iterations= 20
Calibration Max Change=0.05
Calibration Tolerance=0.2
Calibration Maximum=1.5
Calibration Minimum=0.5
Calibration Optimization Method= 1
WQ AD Non Conservative
WQ ULTIMATE=-1
WQ Max Comp Step=1HOUR
WQ Output Interval=15MIN
WQ Output Selected Increments= 0
WQ Output face flow=0
WQ Output face velocity=0
WQ Output face area=0
WQ Output face dispersion=0
WQ Output cell volume=0
WQ Output cell surface area=0
WQ Output cell continuity=0
WQ Output cumulative cell continuity=0
WQ Output face conc=0
WQ Output face dconc_dx=0
WQ Output face courant=0
WQ Output face peclet=0
WQ Output face adv mass=0
WQ Output face disp mass=0
WQ Output cell mass=0
WQ Output cell source sink temp=0
WQ Output nsm pathways=0
WQ Output nsm derived pathways=0
WQ Output MaxMinRange=-1
WQ Daily Max Min Mean=-1
WQ Daily Range=0
WQ Daily Time=0
WQ Create Restart=0
WQ Fixed Restart=0
WQ System Summary=0
WQ Write To DSS=0
WQ Use Fixed Temperature=0
Sorting and Armoring Iterations= 10
XS Update Threshold= 0.02
Bed Roughness Predictor= 0
Hydraulics Update Threshold= 0.02
Energy Slope Method= 1
Volume Change Method= 1
Sediment Retention Method= 0
XS Weighting Method= 0
Number of US Weighted Cross Sections= 1
Number of DS Weighted Cross Sections= 1
Upstream XS Weight=0
Main XS Weight=1
Downstream XS Weight=0
Number of DS XS's Weighted with US Boundary= 1
Upstream Boundary Weight= 1
Weight of XSs Associated with US Boundary= 0
Number of US XS's Weighted with DS Boundary= 1
Downstream Boundary Weight= 0.5
Weight of XSs Associated with DS Boundary= 0.5
Percentile Method= 0
Sediment Output Level= 3
Mass or Volume Output= 0
Output Increment Type= 1
Profile and TS Output Increment= 1
XS Output Flag= 0
XS Output Increment= 10
Write Gradation File= 0
Read Gradation Hotstart= 0
Write HDF5 File= 1
Write Binary Output= 1
Write DSS Sediment File= 0
SV Curve= 0
Specific Gage Flag= 0

--- BUCKLICKRN.f01 (steady flow) ---

Flow Title=Flows
Program Version=5.07
Number of Profiles= 6
Profile Names=P100yr,P10yr,P25yr,P50yr,P500yr,P101yr
River Rch & RM=BUCKLICKRN,Main            ,10378
     725     338     479     598    1066     883
River Rch & RM=BUCKLICKRN,Main            ,10124
     810     377     534     668    1191     985
River Rch & RM=BUCKLICKRN,Main            ,5658
     916     425     603     755    1349    1115
River Rch & RM=BUCKLICKRN,Main            ,2962
    1023     475     673     843    1509    1246
River Rch & RM=BUCKLICKRN,Main            ,5
    1608     741    1054    1323    2383    1957
Boundary for River Rch & Prof#=BUCKLICKRN,Main            , 1
Up Type= 0
Dn Type= 1
Dn Known WS=1489.59
Boundary for River Rch & Prof#=BUCKLICKRN,Main            , 2
Up Type= 0
Dn Type= 1
Dn Known WS=1487.85
Boundary for River Rch & Prof#=BUCKLICKRN,Main            , 3
Up Type= 0
Dn Type= 1
Dn Known WS=1488.67
Boundary for River Rch & Prof#=BUCKLICKRN,Main            , 4
Up Type= 0
Dn Type= 1
Dn Known WS=1489.32
Boundary for River Rch & Prof#=BUCKLICKRN,Main            , 5
Up Type= 0
Dn Type= 1
Dn Known WS=1490.16
Boundary for River Rch & Prof#=BUCKLICKRN,Main            , 6
Up Type= 0
Dn Type= 1
Dn Known WS=1489.87
DSS Import GetInterval= 0
DSS Import GetPeak= 0
DSS Import FillOption= 0

--- BUCKLICKRN.g01 (geometry) ---

Geom Title=Geometry
Program Version=5.07

River Reach=BUCKLICKRN      ,Main
Reach XY= 30
     2502025.138      633067.368     2501768.748      633325.724
     2501503.311      633381.729     2501458.615      633844.223
     2501063.955      634503.718     2501021.955      634872.462
     2500924.115      635009.253     2501047.494      635238.521
     2501026.217       635434.33     2501089.809      635541.072
     2500954.993      635724.794      2501026.41      635895.063
     2500957.331      636120.105     2501034.433      636378.459
     2500923.568      636520.393      2500897.61      636699.426
     2501015.589      637109.505     2500899.642      637323.441
     2501113.827      637824.331     2501096.774      637997.405
     2500992.525       638112.14      2501147.36      638595.021
     2501281.362      638858.328     2501420.938      638993.044
     2501374.481      639189.625     2501447.943      639851.081
     2501532.428      640105.991     2501398.834      640543.287
     2501527.729       641641.572501258.28766788642201.122833772

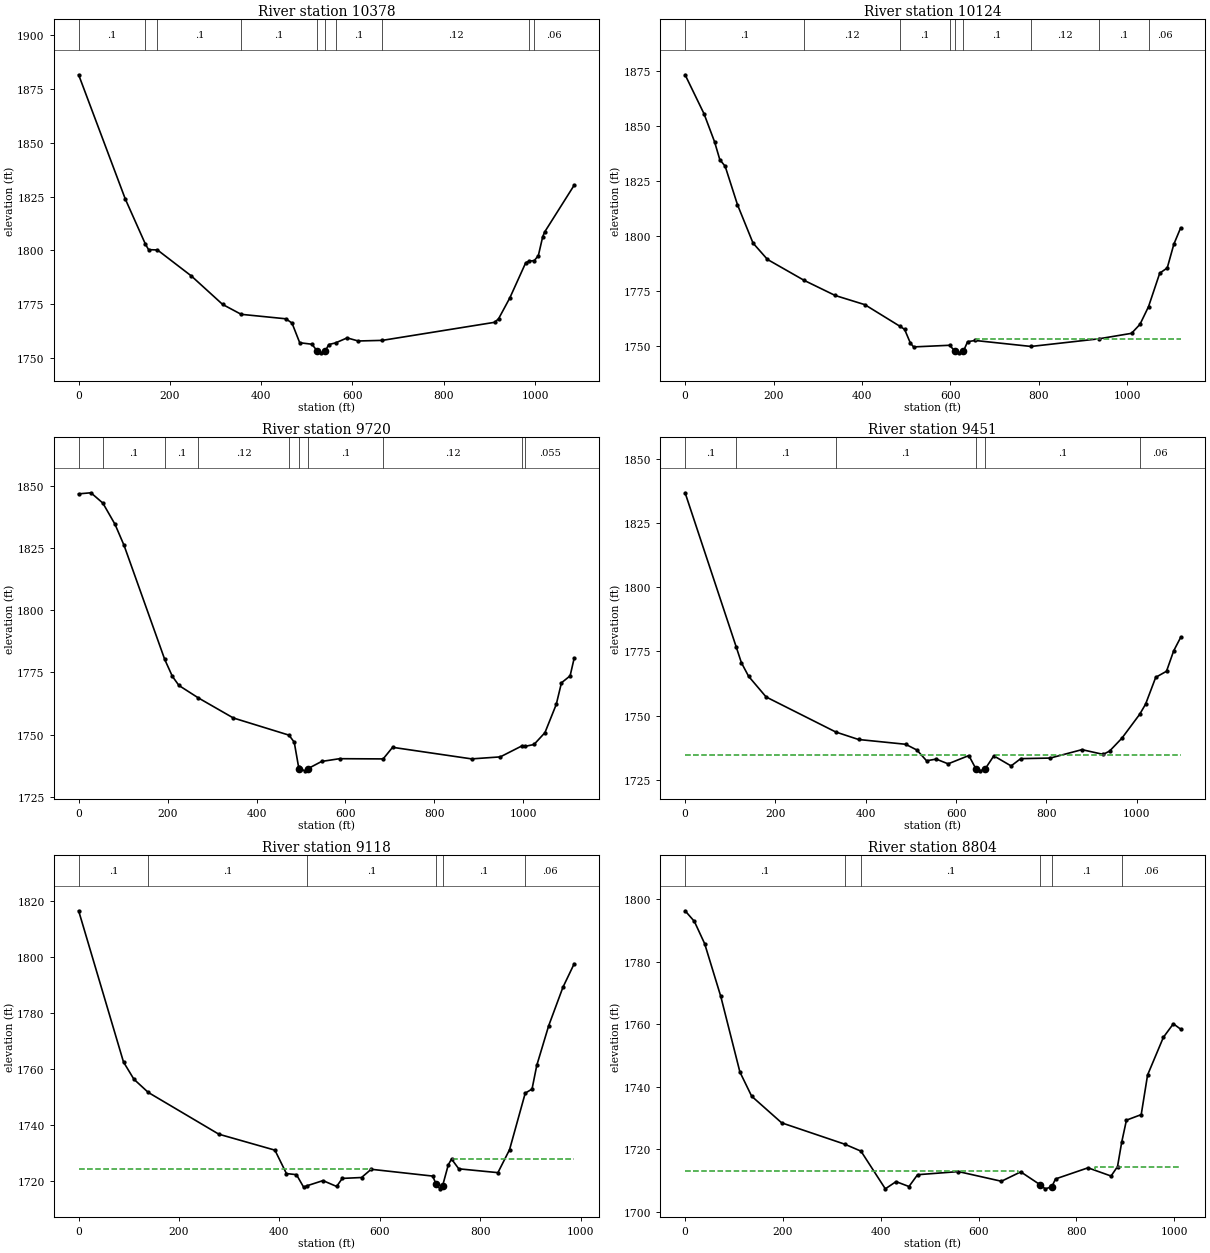
Type RM Length L Ch R = 1 ,10378   ,256.8,254.4,252.5
XS GIS Cut Line= 4
2501737.06476632632622.7320162212501959.28698859633001.204238459
2502105.12032187633292.8709051312502292.62032187633553.287571788
#Sta/Elev= 30
       01881.573 102.2321823.899  146.41 1802.91 153.2561800.381  172.711800.234
246.83771788.188315.60481774.935  356.211770.351454.19161768.274 467.6081766.269
 484.4641757.161511.29681756.462   522.31753.447532.16681752.469   540.71753.429
548.10641756.314  562.981757.085588.35571759.413612.66521757.971  665.391758.257
911.52391766.646920.2687 1768.31944.91341777.996979.65261794.275  986.781795.054
   998.51795.2961007.3641797.6181016.9061806.3571021.0561808.5341085.8771830.293
#Mann= 10 ,-1 , 0
       0      .1       0  146.41      .1       0  172.71      .1       0
  356.21      .1       0   522.3    .045       0   540.7      .1       0
  562.98      .1       0  665.39     .12       0  986.78    .055       0
   998.5     .06       0
Bank Sta=522.3,540.7
XS Rating Curve= 0 ,0
Exp/Cntr(USF)=0,0
Exp/Cntr=0.3,0.1

Type RM Length L Ch R = 1 ,10124   ,405.3,403.4,398.8
XS GIS Cut Line= 4
2501469.70365521632751.2042384592501709.28698856633115.787571788
2501907.20365521633365.787571773 2502136.3703219633650.509794012
#Sta/Elev= 30
       01873.46342.70241 1855.7866.634281843.011 78.51061834.88290.566161831.908
118.4341 1814.42153.60721796.975186.29371789.536  269.511779.996339.45771773.156
406.46691768.986  486.05 1759.13496.3354 1757.77509.49461751.514516.74241749.785
  598.161750.531   610.41747.825618.89681747.093   629.51747.893638.82921752.164
655.91411752.712  782.331749.996  935.321753.4591009.5651755.9581028.7041760.067
 1047.951768.071 1073.361783.312 1090.291785.6641105.2581796.4721120.6091803.888
#Mann= 9 ,-1 , 0
       0      .1       0  269.51     .12       0  486.05      .1       0
  598.16      .1       0   610.4    .045       0   629.5      .1       0
  782.33     .12       0  935.32      .1       0 1047.95     .06       0
#XS Ineff= 2 , 0
                          658.44         1753.43
Permanent Ineff=
       F       F
Bank Sta=610.4,629.5
XS Rating Curve= 0 ,0
Exp/Cntr(USF)=0,0
Exp/Cntr=0.3,0.1

Type RM Length L Ch R = 1 ,9720    ,272.6,269.9,267.1
XS GIS Cut Line= 4
2501084.28698859633119.2597939972501417.62032187 633358.84312734
 2501744.0092108633584.5375717732501959.28698859633803.287571773
#Sta/Elev= 30
       01846.78227.657181847.215   54.521843.05881.843341834.529102.17171826.052
   193.61780.207210.71821773.444225.53621769.754   268.91764.784347.84811756.687
  472.921749.791484.81641746.948494.54281737.003   496.61736.354509.13231735.436
   516.21736.371546.47311739.216586.72441740.318   684.7 1740.23705.9673 1744.89
883.5828 1740.24948.08741741.046  997.931745.571 1004.391745.2961023.8861746.025
1048.5171750.7871073.9741762.154 1085.621770.8161105.0881773.6151114.2371780.722
#Mann= 10 ,-1 , 0
       0      .1       0   54.52      .1       0   193.6      .1       0
   268.9     .12       0  472.92      .1       0   496.6    .045       0
   516.2      .1       0   684.7     .12       0  997.93      .1       0
 1004.39    .055       0
Bank Sta=496.6,516.2
XS Rating Curve= 0 ,0
Exp/Cntr(USF)=0,0
Exp/Cntr=0.3,0.1

Type RM Length L Ch R = 1 ,9451    ,330.4,332.3,333.3
XS GIS Cut Line= 4
2500830.81476635633483.8431273552501320.39809966633629.676460668
2501646.78698859633747.7320162212501830.81476632633900.509794012
#Sta/Elev= 30
       01836.689  112.971776.855124.59421770.633140.67311765.309179.39571757.294
  333.581743.672383.90631740.761488.24841738.901513.33741736.648534.60551732.485
555.87361733.135582.34531731.296628.18511734.512   643.71729.412653.70671728.572
   664.61729.403683.48211734.398721.7646 1730.48743.03271733.316 808.4121733.538
878.66561736.814925.49211734.971939.67461736.237 967.0451741.266 1006.331750.533
1019.425 1754.481041.9351764.9311065.8221767.2881081.7031775.2361097.1051780.437
#Mann= 6 ,-1 , 0
       0      .1       0  112.97      .1       0  333.58      .1       0
   643.7    .045       0   664.6      .1       0 1006.33     .06       0
#XS Ineff= 2 , 0
          623.87 1734.83  688.07         1734.83
Permanent Ineff=
       F       F
Bank Sta=643.7,664.6
XS Rating Curve= 0 ,0
Exp/Cntr(USF)=0,0
Exp/Cntr=0.3,0.1

Type RM Length L Ch R = 1 ,9118    ,316.6,314.3,311.8
XS GIS Cut Line= 4
2500757.89809966633619.2597939972501066.92587745633778.982016236
2501459.28698856634039.3986828922501601.64809969634129.676460683
#Sta/Elev= 30
       01816.53489.407931762.595 110.1871756.458  138.811751.751 279.3881736.864
 391.0991731.176414.03721722.825434.06251722.436448.46511717.924  454.251718.434
486.87211720.315514.06521718.229 525.2791721.098563.68591721.419582.88941724.355
705.48551721.929   712.51718.941719.9137 1717.38   725.31718.534736.51721725.935
742.99871728.005757.42691724.519835.41241723.156858.59991731.342  889.841751.503
903.39731752.963912.87021761.427936.55271775.536964.97161789.265 987.3551797.634
#Mann= 6 ,-1 , 0
       0      .1       0  138.81      .1       0  454.25      .1       0
   712.5    .045       0   725.3      .1       0  889.84     .06       0
#XS Ineff= 2 , 0
          581.62 1724.58  743.48          1727.9
Permanent Ineff=
       F       F
Bank Sta=712.5,725.3
XS Rating Curve= 0 ,0
Exp/Cntr(USF)=0,0
Exp/Cntr=0.3,0.1

Type RM Length L Ch R = 1 ,8804    ,310.8,311.1,304.9
XS GIS Cut Line= 4
2500532.20365524633928.2875717882500841.23143303634074.120905116
2501344.70365521634303.2875717882501452.34254414634351.898682907
#Sta/Elev= 30
       01796.35618.889691792.969 39.92441785.85772.978941768.929112.04341744.765
136.08311737.016197.42341728.499  326.261721.676  359.531719.442409.29581707.387
431.27021709.695457.63941708.126475.21891711.904558.72161712.903 646.619 1709.81
686.17291712.815   725.71708.702736.05651707.384   749.61708.031757.19771710.553
823.64151714.113870.75751711.481883.94211714.496  892.511722.302902.17411729.357
932.40941731.136945.40271743.812977.7623 1755.88998.07061760.191 1012.99 1758.48
#Mann= 6 ,-1 , 0
       0      .1       0  326.26      .1       0  359.53      .1       0
   725.7    .045       0   749.6      .1       0  892.51     .06       0
#XS Ineff= 2 , 0
          681.48  1713.1  838.21         1714.23
Permanent Ineff=
       F       F
Bank Sta=725.7,749.6
XS Rating Curve= 0 ,0
Exp/Cntr(USF)=0,0
Exp/Cntr=0.3,0.1

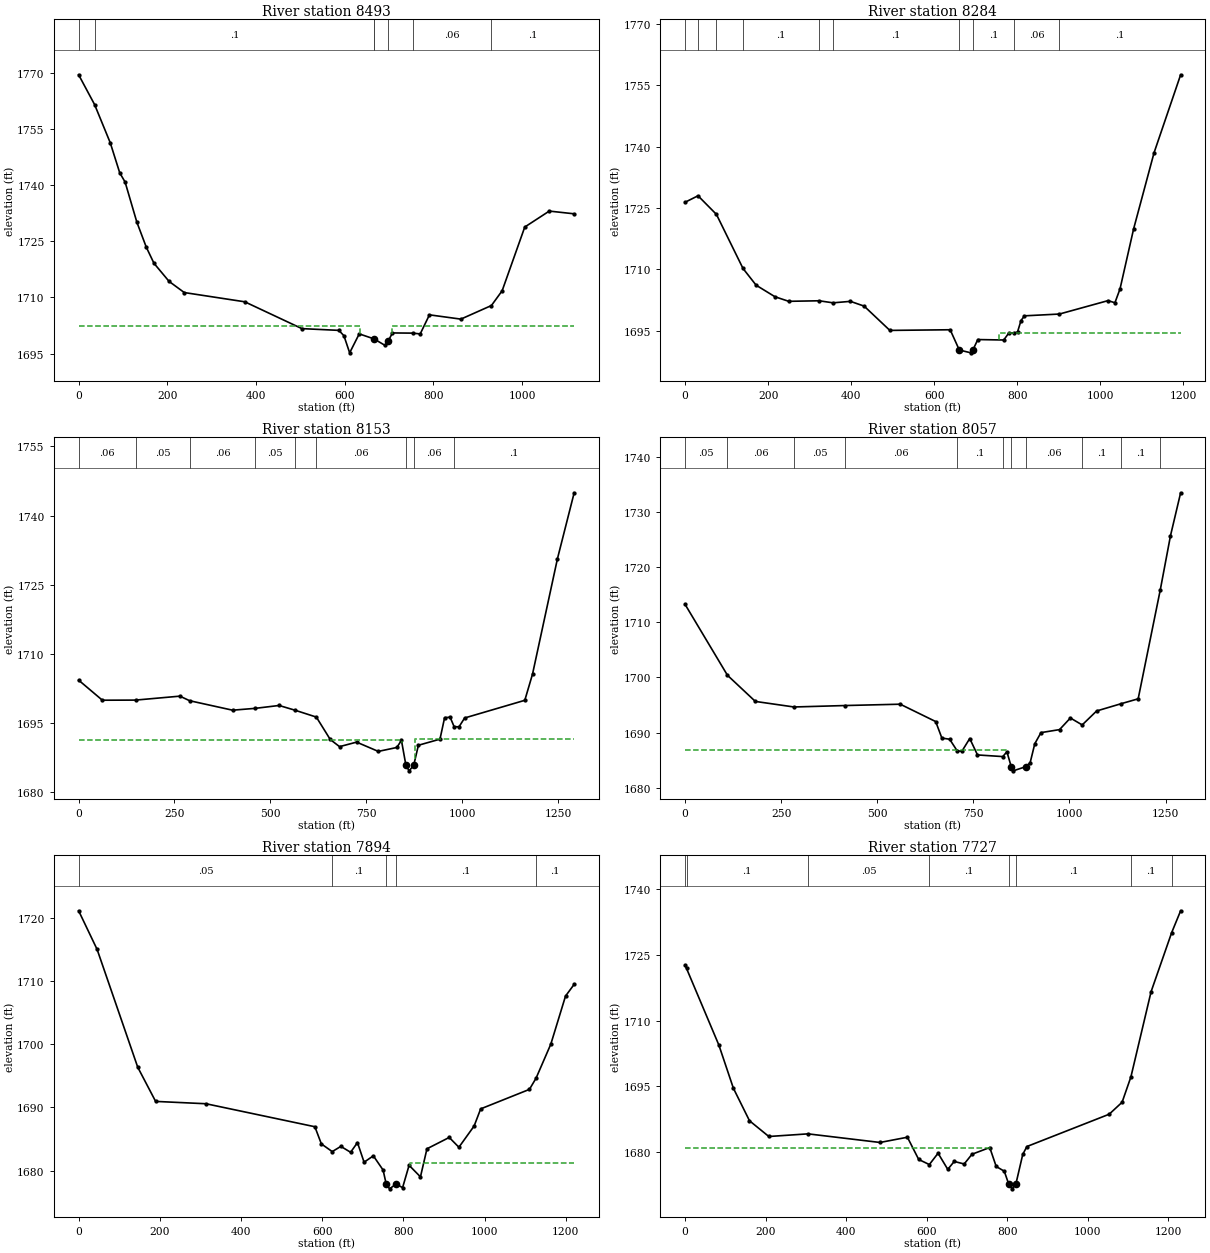
Type RM Length L Ch R = 1 ,8493    ,203.9,208.4,201.7
XS GIS Cut Line= 4
2500428.03698859634282.454238445  2500903.731433634463.009794012
 2501261.3703219634567.1764606832501483.59254411634487.315349564
#Sta/Elev= 30
       01769.475   36.041761.50471.351651751.29992.743871743.264104.78121740.824
131.24991730.122152.64211723.405169.9087 1719.12203.98341714.284 238.2111711.308
374.59481708.838503.47441701.673586.93861701.204598.25741699.767611.16331695.204
 632.7671700.269666.09671698.929   666.11698.928691.09391697.182   698.31698.438
707.75881700.519  753.331700.469 770.2521700.257791.08311705.353861.9088 1704.21
  930.851707.842955.02661711.7831006.0321728.8061061.2881733.0681117.4451732.337
#Mann= 7 ,-1 , 0
       0      .1       0   36.04      .1       0666.0967    .045       0
   666.1    .045       0   698.3      .1       0  753.33     .06       0
  930.85      .1       0
#XS Ineff= 2 , 0
          633.74 1702.25  706.17         1702.25
Permanent Ineff=
       F       F
Bank Sta=666.1,698.3
XS Rating Curve= 0 ,0
Exp/Cntr(USF)=0,0
Exp/Cntr=0.3,0.1

Type RM Length L Ch R = 1 ,8284    ,132,131.7,116.9
XS GIS Cut Line= 4
 2500369.0092108634522.0375717882500896.78698859634657.454238445
2501198.87032187634744.259793997 2501525.2592108634817.176460668
#Sta/Elev= 30
       01726.411   31.111727.992   75.481723.448  139.491710.246171.10431706.159
216.52951703.338249.56611702.226  322.911702.357  356.241701.856398.23051702.217
 431.2671701.052493.21051695.125638.47191695.283   660.51690.338688.41441689.647
   693.21690.351705.06181692.891767.4899 1692.78779.97551694.516  792.971694.451
800.7849 1694.76809.10861697.528817.4324 1698.68  901.641699.1191018.8991702.397
1035.2931701.8681047.5891705.2491080.3781719.9181129.5611738.4871193.6161757.531
#Mann= 10 ,-1 , 0
       0     .05       0   31.11      .1       0   75.48     .05       0
  139.49      .1       0  322.91     .05       0  356.24      .1       0
   660.5    .045       0   693.2      .1       0  792.97     .06       0
  901.64      .1       0
#XS Ineff= 2 , 0
                          755.56         1694.61
Permanent Ineff=
       F       F
Bank Sta=660.5,693.2
XS Rating Curve= 0 ,0
Exp/Cntr(USF)=0,0
Exp/Cntr=0.5,0.3

Type RM Length L Ch R = 1 ,8153    ,95.9,95.5,86
XS GIS Cut Line= 4
2500181.50921077634692.1764606832500962.75921077634806.759793997
2501205.81476632634831.0653495492501462.75921077634858.843127355
#Sta/Elev= 30
       01704.22961.890951699.871  148.411699.896264.03061700.753  289.52 1699.76
401.48561697.702  460.911698.106522.76941698.728  565.07 1697.68  619.941696.206
656.1816 1691.34680.43841689.781724.90911690.766781.50821688.749829.79331689.601
841.85321691.148   853.61685.698861.95291684.527   873.81685.723886.07261690.085
942.35191691.411954.41181696.071968.78541696.186  979.171694.132991.92291694.083
1006.6711696.0111163.5571699.8491183.6741705.5321248.7781730.6421292.3181744.937
#Mann= 9 ,-1 , 0
       0     .06       0  148.41     .05       0  289.52     .06       0
  460.91     .05       0  565.07      .1       0  619.94     .06       0
   853.6    .045       0   873.8     .06       0  979.17      .1       0
#XS Ineff= 2 , 0
          843.07 1691.24  877.64         1691.37
Permanent Ineff=
       F       F
Bank Sta=853.6,873.8
XS Rating Curve= 0 ,0
Exp/Cntr(USF)=0,0
Exp/Cntr=0.5,0.3

Type RM Length L Ch R = 1 ,8057    ,161.5,162.9,167.9
XS GIS Cut Line= 4
2500136.37032187634820.648682907  2500778.731433634865.787571773
2501157.20365521634910.9264606832501421.09254411634924.815349564
#Sta/Elev= 30
       01713.255  110.23  1700.4182.82441695.658  283.271694.651   416.31694.913
559.75161695.156652.01551692.007668.12891689.007688.27061688.805  708.381686.646
720.49741686.656740.63921688.931760.78091685.952  826.681685.653837.31951686.536
   848.61683.811853.69781683.068   886.41683.824897.74481684.524909.8298 1687.98
925.9432    1690974.28341690.5461002.4821692.655 1033.191691.3961070.7041693.924
 1134.811695.2531178.8541696.132 1236.431715.913 1262.971725.7271289.3541733.506
#Mann= 11 ,-1 , 0
       0     .05       0  110.23     .06       0  283.27     .05       0
   416.3     .06       0  708.38      .1       0  826.68     .06       0
   848.6    .045       0   886.4     .06       0 1033.19      .1       0
 1134.81      .1       0 1236.43      .1       0
#XS Ineff= 2 , 0
          835.48  1686.9
Permanent Ineff=
       F       F
Bank Sta=848.6,886.4
XS Rating Curve= 0 ,0
Exp/Cntr(USF)=0,0
Exp/Cntr=0.5,0.3

Type RM Length L Ch R = 1 ,7894    ,165.8,167.5,157.8
XS GIS Cut Line= 4
2500157.20365521635008.1486828922500723.17587748635025.509793997
2501091.23143303635032.4542384592501375.95365521635004.676460683
#Sta/Elev= 30
       01721.13445.56281 1715.01145.60981696.362189.63051690.959313.68891690.589
581.81041686.949597.8132 1684.23   624.61683.013645.82181683.839 669.8261682.906
686.72081684.444703.03141681.334 725.8361682.344749.84031680.096   757.61677.852
765.84311677.119   781.81677.891797.84881677.305813.85171680.846841.85661679.016
857.85951683.458912.71421685.253936.53081683.703974.06071687.067990.13671689.776
1110.2161692.863 1126.54 1694.631162.953 1700.031199.1241707.6281220.4331709.492
#Mann= 5 ,-1 , 0
       0     .05       0   624.6      .1       0   757.6    .045       0
   781.8      .1       0 1126.54      .1       0
#XS Ineff= 2 , 0
                          816.19         1681.18
Permanent Ineff=
       F       F
Bank Sta=757.6,781.8
XS Rating Curve= 0 ,0
Exp/Cntr(USF)=0,0
Exp/Cntr=0.3,0.1

Type RM Length L Ch R = 1 ,7727    ,247.3,247.8,248.2
XS GIS Cut Line= 4
 2500198.8703219635178.2875717882500761.37032187635174.815349549
2501181.50921077635147.0375717732501428.03698859635153.982016236
#Sta/Elev= 30
       01722.726    3.571721.94883.876311704.431 119.8771694.573159.87781687.137
207.87871683.542  305.111684.146483.88391682.178551.89521683.375579.92331678.295
  606.321677.127628.02811679.719652.08061676.031668.11551677.838692.84311677.261
712.21151679.486756.30761681.022772.34251676.688792.38621675.606   803.2 1672.71
811.90061671.579   821.21672.695838.22141679.443848.50851681.248 1052.831688.634
1084.8431691.367 1106.771697.1741156.8711716.653 1207.891730.1321230.1931735.133
#Mann= 8 ,-1 , 0
       0     .05       0    3.57      .1       0  305.11     .05       0
  606.32      .1       0   803.2    .045       0   821.2      .1       0
 1106.77      .1       0 1207.89      .1       0
#XS Ineff= 2 , 0
          758.57 1680.85
Permanent Ineff=
       F       F
Bank Sta=803.2,821.2
XS Rating Curve= 0 ,0
Exp/Cntr(USF)=0,0
Exp/Cntr=0.3,0.1

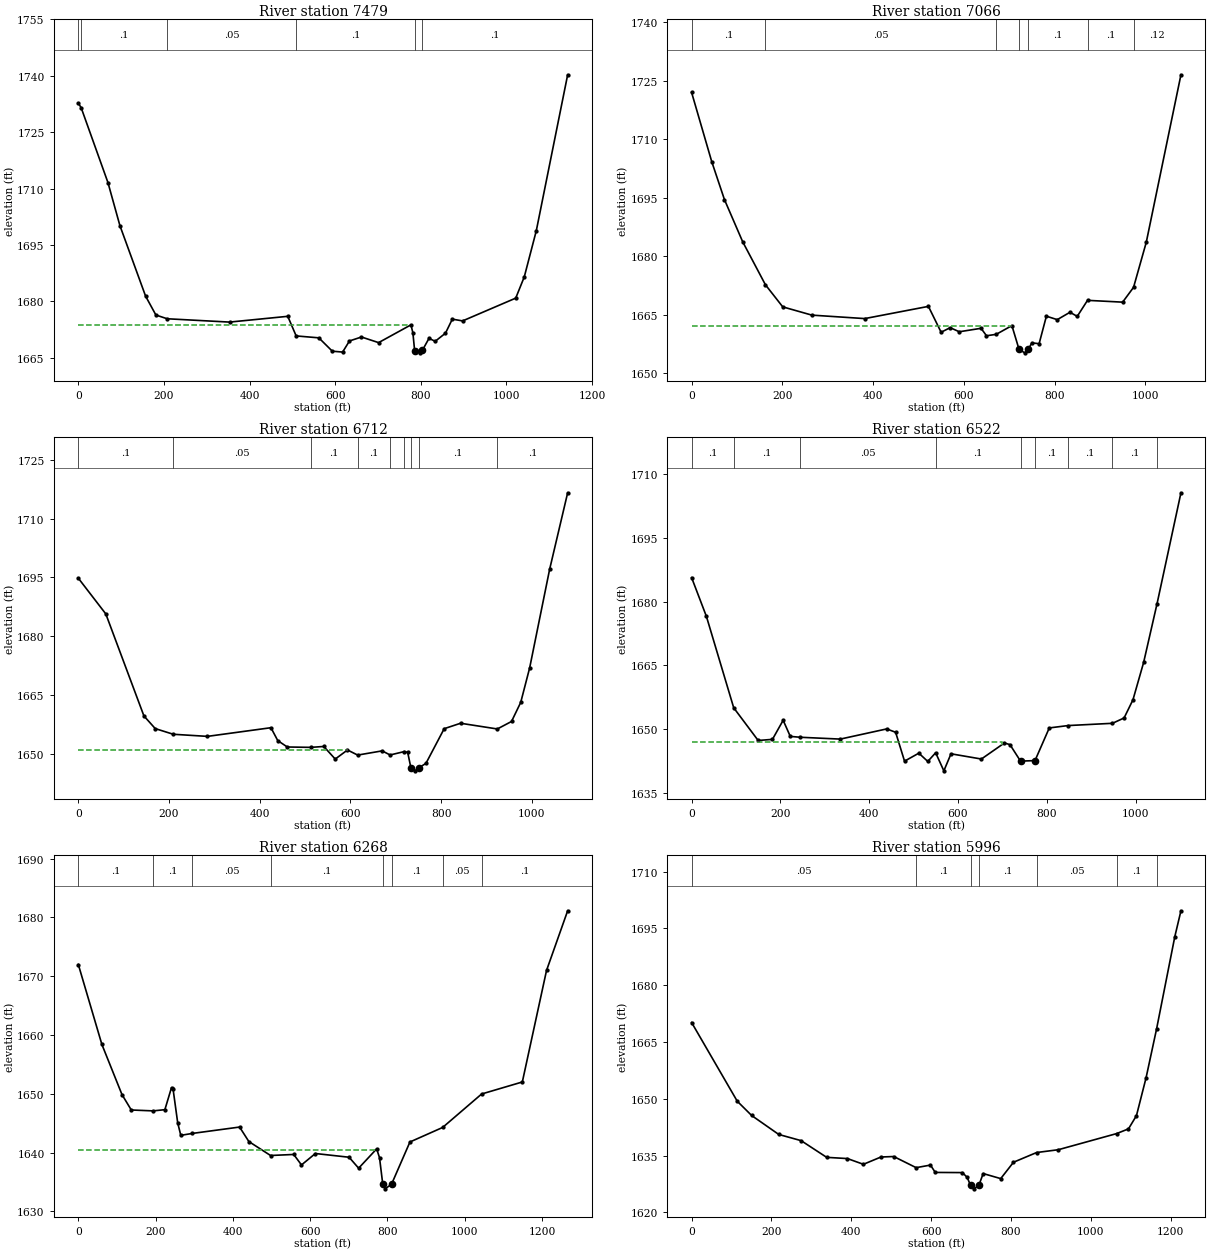
Type RM Length L Ch R = 1 ,7479    ,412.2,413.4,411
XS GIS Cut Line= 4
2500233.59254414635410.9264606682500698.87032187635407.454238459
2501191.92587745635386.6209051162501375.95365521635379.676460683
#Sta/Elev= 30
       01732.734    6.561731.54869.154421711.625 97.15521700.151157.15691681.384
181.15751676.375  207.551675.373353.16231674.488489.18681676.024  508.821670.807
 561.7431670.299593.27951666.743 617.3011666.512633.31521669.466661.3402 1670.52
701.37591669.025776.8537 1673.75781.44731671.646   785.51666.891797.46151666.307
   803.51666.952819.10751670.169833.49371669.374857.51511671.531873.52941675.271
897.55081674.803 1021.651680.8651041.6641686.5311069.6841698.7881142.9451740.291
#Mann= 6 ,-1 , 0
       0     .05       0    6.56      .1       0  207.55     .05       0
  508.82      .1       0   785.5    .045       0   803.5      .1       0
#XS Ineff= 2 , 0
          772.02 1673.78
Permanent Ineff=
       F       F
Bank Sta=785.5,803.5
XS Rating Curve= 0 ,0
Exp/Cntr(USF)=0,0
Exp/Cntr=0.3,0.1

Type RM Length L Ch R = 1 ,7066    ,352.3,354,353.9
XS GIS Cut Line= 4
2500226.64809966635692.1764606682500702.34254414635733.843127355
 2501119.0092108635733.8431273552501303.03698859635744.259793997
#Sta/Elev= 30
       01721.96744.265781704.27772.372991694.522112.52611683.726  162.64 1672.71
200.86311667.037265.10811664.921381.55221664.035521.91831667.164549.91831660.533
569.91831661.711589.91831660.659637.91831661.548649.91831659.636  671.351659.999
705.91831662.237   721.51656.216733.9183 1655.26   742.11656.187749.91831657.813
765.91831657.606781.91831664.648805.91831663.766833.91831665.654849.91831664.603
  872.581668.709950.00751668.247  974.051672.0431002.0911683.5941078.5051726.501
#Mann= 7 ,-1 , 0
       0      .1       0  162.64     .05       0  671.35      .1       0
   721.5    .045       0   742.1      .1       0  872.58      .1       0
  974.05     .12       0
#XS Ineff= 2 , 0
          706.17 1662.25
Permanent Ineff=
       F       F
Bank Sta=721.5,742.1
XS Rating Curve= 0 ,0
Exp/Cntr(USF)=0,0
Exp/Cntr=0.3,0.1

Type RM Length L Ch R = 1 ,6712    ,191.8,190,186.9
XS GIS Cut Line= 4
2500230.12032187636018.565349564  2500684.981433636022.037571773
2501112.06476635636067.176460668 2501306.5092108636067.176460668
#Sta/Elev= 30
       01694.81260.626481685.714144.62891659.739169.59871656.515  209.431655.071
 284.6331654.536424.63711656.742439.66821653.466460.67011651.832  512.881651.737
541.11571651.967566.38821648.758593.40531651.072  615.821649.773669.82861650.844
   687.31649.799  718.761650.667726.14051650.444   733.11646.593742.2296 1645.76
   751.71646.606766.3633 1647.66806.58611656.495842.69491657.876  923.721656.422
955.0167 1658.33975.30231663.189995.01671671.9841039.0171697.0651078.7811716.567
#Mann= 9 ,-1 , 0
       0      .1       0  209.43     .05       0  512.88      .1       0
  615.82      .1       0   687.3      .1       0  718.76      .1       0
   733.1    .045       0   751.7      .1       0  923.72      .1       0
#XS Ineff= 2 , 0
          594.58 1651.13
Permanent Ineff=
       F       F
Bank Sta=733.1,751.7
XS Rating Curve= 0 ,0
Exp/Cntr(USF)=0,0
Exp/Cntr=0.3,0.1

Type RM Length L Ch R = 1 ,6522    ,246.7,254.1,261.5
XS GIS Cut Line= 4
2500233.59254414636226.8986828922500678.03698859636272.037571788
2501112.06476635636223.4264606682501330.81476635636219.954238459
#Sta/Elev= 30
       01685.65733.323041676.525   94.851654.986149.9198 1647.29182.0844 1647.55
206.20791652.051222.2902 1648.25  244.731648.047334.86631647.615439.40131650.012
459.51831649.226479.64331642.418511.84341644.301531.9684 1642.35  549.691644.394
568.19351640.137584.2936 1644.15652.7188 1642.92704.59581646.701717.11891646.309
   740.91642.427   773.51642.548805.66911650.247  847.991650.803  948.031651.336
 974.1641652.595994.16651656.877 1018.171665.669 1048.391679.502 1102.251705.645
#Mann= 9 ,-1 , 0
       0      .1       0   94.85      .1       0  244.73     .05       0
  549.69      .1       0   740.9    .045       0   773.5      .1       0
  847.99      .1       0  948.03      .1       0 1048.39      .1       0
#XS Ineff= 2 , 0
          699.59 1646.84
Permanent Ineff=
       F       F
Bank Sta=740.9,773.5
XS Rating Curve= 0 ,0
Exp/Cntr(USF)=0,0
Exp/Cntr=0.3,0.1

Type RM Length L Ch R = 1 ,6268    ,276.2,271.4,264.4
XS GIS Cut Line= 4
2500205.81476632636383.148682892  2500903.731433636410.926460683
2501059.98143303636504.6764606682501445.39809966636511.620905116
#Sta/Elev= 30
       01671.99660.978521658.394113.01971649.861137.03871647.245  193.361647.093
223.94351647.298 241.1211651.058245.12421650.828257.13371645.063  265.141642.931
  294.711643.255417.26041644.342441.27941641.875   497.41639.502557.37121639.679
577.38711637.894613.4156 1639.84700.63981639.205725.30751637.341771.9551 1640.63
779.3577 1639.13   787.71634.644793.9351 1633.83   810.51634.622858.07551641.803
  942.661644.273 1043.581649.9671148.8771652.0111211.5041670.9871266.1661681.138
#Mann= 8 ,-1 , 0
       0      .1       0  193.36      .1       0  294.71     .05       0
   497.4      .1       0   787.7    .045       0   810.5      .1       0
  942.66     .05       0 1043.58      .1       0
#XS Ineff= 2 , 0
           770.1 1640.52
Permanent Ineff=
       F       F
Bank Sta=787.7,810.5
XS Rating Curve= 0 ,0
Exp/Cntr(USF)=0,0
Exp/Cntr=0.3,0.1

Type RM Length L Ch R = 1 ,5996    ,338.4,338.4,339.2
XS GIS Cut Line= 4
2500188.45365524636713.0097939972500726.64809969636699.120905116
2501080.81476632636699.1209051162501414.14809966636688.704238445
#Sta/Elev= 30
       0 1670.15114.3294 1649.37150.3414  1645.6218.36411640.586274.3827 1638.95
 338.404 1634.54390.42131634.217430.43461632.702474.44931634.631506.45991634.757
  562.561631.817598.4706  1632.5610.47061630.557678.47061630.513690.47061629.246
   698.91627.123706.70061626.223   719.71627.125730.47061630.261774.47061628.925
806.47061633.248   864.41635.812918.48321636.549 1064.831640.8131094.5691642.063
1114.5791645.5611138.5911655.526 1164.991668.4611210.6261692.8171226.0361699.661
#Mann= 7 ,-1 , 0
       0     .05       0  562.56      .1       0   698.9    .045       0
   719.7      .1       0   864.4     .05       0 1064.83      .1       0
 1164.99      .1       0
Bank Sta=698.9,719.7
XS Rating Curve= 0 ,0
Exp/Cntr(USF)=0,0
Exp/Cntr=0.3,0.1

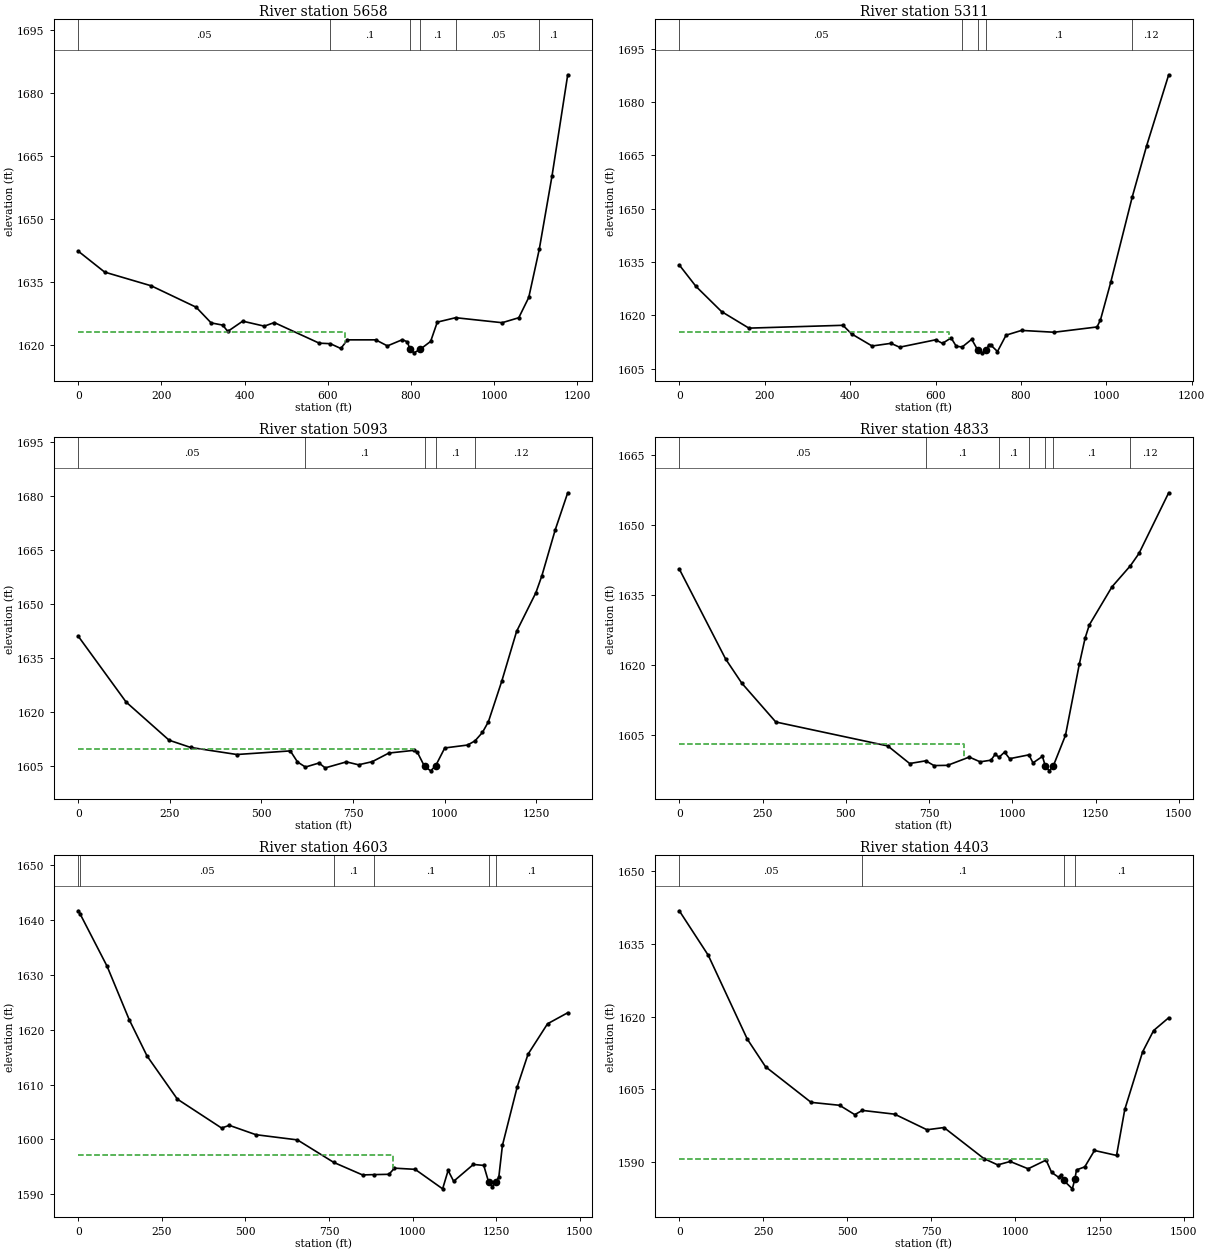
Type RM Length L Ch R = 1 ,5658    ,348.7,347,347.9
XS GIS Cut Line= 4
2500195.39809969637022.037571788  2500809.981433637011.620905116
2501143.31476635637008.1486829072501372.48143303637008.148682907
#Sta/Elev= 30
       01642.33263.356041637.355175.37211634.087283.38761628.989319.39281625.253
347.39681624.719359.39861623.217395.4037 1625.66447.41121624.472471.41461625.326
579.43021620.417  606.211620.295631.43611619.148 647.4371621.208715.44071621.208
743.44221619.764779.4442 1621.25791.4448 1620.74   797.81618.953807.44571618.112
   822.51618.965847.44781620.837863.44871625.433  907.551626.4861019.4531625.295
1059.4531626.4791083.4531631.311  1108.71642.7681139.4531660.292 1177.191684.384
#Mann= 6 ,-1 , 0
       0     .05       0  606.21      .1       0   797.8    .045       0
   822.5      .1       0  907.55     .05       0  1108.7      .1       0
#XS Ineff= 2 , 0
          640.33 1623.14
Permanent Ineff=
       F       F
Bank Sta=797.8,822.5
XS Rating Curve= 0 ,0
Exp/Cntr(USF)=0,0
Exp/Cntr=0.3,0.1

Type RM Length L Ch R = 1 ,5311    ,220,217.6,215.4
XS GIS Cut Line= 4
2500191.92587748637372.7320162362500615.53698856637351.898682892
2501105.12032187637299.8153495642501334.28698859637285.926460683
#Sta/Elev= 30
       01634.17938.937681628.179 98.93861621.094163.01591616.438383.28191617.233
 403.3061614.826451.48471611.416 495.7331612.165515.84581611.079600.31981613.156
616.41011612.156636.52291613.691648.59061611.337   662.51611.144684.79381613.294
   698.41610.388708.92921609.495   718.81610.167725.01951611.759729.04211611.725
745.13241609.869765.24521614.462801.44841615.795877.87721615.281978.20681616.766
986.22151618.7191010.266 1629.27 1060.871653.369 1094.421667.6851146.0561687.621
#Mann= 5 ,-1 , 0
       0     .05       0   662.5      .1       0   698.4    .045       0
   718.8      .1       0 1060.87     .12       0
#XS Ineff= 2 , 0
          631.27  1615.4
Permanent Ineff=
       F       F
Bank Sta=698.4,718.8
XS Rating Curve= 0 ,0
Exp/Cntr(USF)=0,0
Exp/Cntr=0.3,0.1

Type RM Length L Ch R = 1 ,5093    ,257.8,260.4,262
XS GIS Cut Line= 5
2500144.10592916637403.657769858 2500497.9579766637652.840372842
2500921.09254414637539.398682907 2501073.8703219 637483.84312734
2501372.48143303637435.232016236
#Sta/Elev= 30
       0 1641.05 130.4271622.787 247.8421612.177 306.5491610.169 432.7851608.205
 578.7121609.207 598.3061606.134 619.9571604.719 657.0891605.844 673.7931604.483
 731.7711606.159 764.9011605.348 802.1721606.205 847.7261608.609 915.1841609.354
  925.611608.813     9451604.914 962.0031603.666   975.6 1605.111000.3091610.025
1062.6831610.8361082.946    1612 1103.211614.344 1119.421617.3061155.894 1628.57
1196.4211642.4261249.1051653.1821265.3161657.844 1301.79 1670.62 1335.971680.943
#Mann= 5 ,-1 , 0
       0     .05       0 619.957      .1       0     945    .045       0
   975.6      .1       01082.946     .12       0
#XS Ineff= 2 , 0
          917.16 1609.79
Permanent Ineff=
       F       F
Bank Sta=945,975.6
XS Rating Curve= 0 ,0
Exp/Cntr(USF)=0,0
Exp/Cntr=0.3,0.1

Type RM Length L Ch R = 1 ,4833    ,224.8,230.1,239.3
XS GIS Cut Line= 5
2500130.10401701637479.6909136972500577.65789047637848.674446926
2500969.70365524637772.0375717882501164.14809969637737.315349564
2501438.45365521637636.620905131
#Sta/Elev= 30
       01640.566  139.121621.257 187.3841616.099 289.7191607.743 625.9871602.602
 691.5891598.832 740.1061599.413 764.5611598.394 805.3181598.442 870.5291600.218
 903.1351599.197  935.74 1599.55 947.9671600.775 960.1951600.197 976.4971601.276
 991.7411599.8711049.6461600.6951061.8351598.9681090.2781600.362  1098.41598.393
1110.5951597.263  1122.81598.3181159.3541604.8781201.1041620.2111218.1481625.699
1230.9311628.5711299.1061636.7561354.4991641.2861380.0651643.9111469.2361656.922
#Mann= 7 ,-1 , 0
       0     .05       0 740.106      .1       0 960.195      .1       0
1049.646      .1       0  1098.4    .045       0  1122.8      .1       0
1354.499     .12       0
#XS Ineff= 2 , 0
           853.6 1602.96
Permanent Ineff=
       F       F
Bank Sta=1098.4,1122.8
XS Rating Curve= 0 ,0
Exp/Cntr(USF)=0,0
Exp/Cntr=0.3,0.1

Type RM Length L Ch R = 1 ,4603    ,218.6,199.6,193.1
XS GIS Cut Line= 5
2500114.27705746637508.3562022482500639.14068117638042.231380614
2501049.56476635637942.1764606832501136.37032187637997.732016221
2501323.87032187637966.482016236
#Sta/Elev= 30
       0 1641.68   4.9521641.152  86.2521631.547 152.0351621.866  205.491615.232
  296.291607.358 428.5891602.091  451.861602.578 531.2911600.875 655.5141599.927
 764.3461595.821 850.4111593.541 884.127  1593.6 929.4161593.656 945.8841594.776
1007.6411594.5631089.9841591.0081106.4531594.3671122.9221592.3841182.0121595.455
1213.0251595.276  1227.5 1592.271239.0871591.3471248.499 1592.341257.9971593.099
1268.9031598.9271313.0781609.5761345.5191615.5451403.8371621.085 1464.261623.097
#Mann= 6 ,-1 , 0
       0      .1       0   4.952     .05       0 764.346      .1       0
 884.127      .1       0  1227.5    .045       01248.499      .1       0
#XS Ineff= 2 , 0
          942.93 1597.13
Permanent Ineff=
       F       F
Bank Sta=1227.5,1248.499
XS Rating Curve= 0 ,0
Exp/Cntr(USF)=0,0
Exp/Cntr=0.3,0.1

Type RM Length L Ch R = 1 ,4403    ,263.5,261.1,262.7
XS GIS Cut Line= 4
2500105.00544678637534.6480024092500757.89809966638185.232016236
2501108.59254414638101.8986828922501278.73143303638067.176460668
#Sta/Elev= 30
       01641.852  86.2551632.643 202.2211615.333 256.5651609.616 392.0891602.254
 476.7921601.649 521.967 1599.72 544.5551600.592 640.6271599.813 736.794 1596.59
  787.37 1597.05 905.9541590.643 947.2371589.327  984.241590.0331037.6881588.526
1091.1361590.3271107.5811587.7751128.1381586.7821136.3611587.283  1143.61586.105
1169.252 1584.38  1176.81586.4441181.5861588.2871206.2541588.9291235.0341592.311
1300.6851591.2831325.1791600.7871378.2511612.6941410.9111617.0951455.8041619.743
#Mann= 4 ,-1 , 0
       0     .05       0 544.555      .1       0  1143.6    .045       0
  1176.8      .1       0
#XS Ineff= 2 , 0
          1093.8 1590.64
Permanent Ineff=
       F       F
Bank Sta=1143.6,1176.8
XS Rating Curve= 0 ,0
Exp/Cntr(USF)=0,0
Exp/Cntr=0.3,0.1

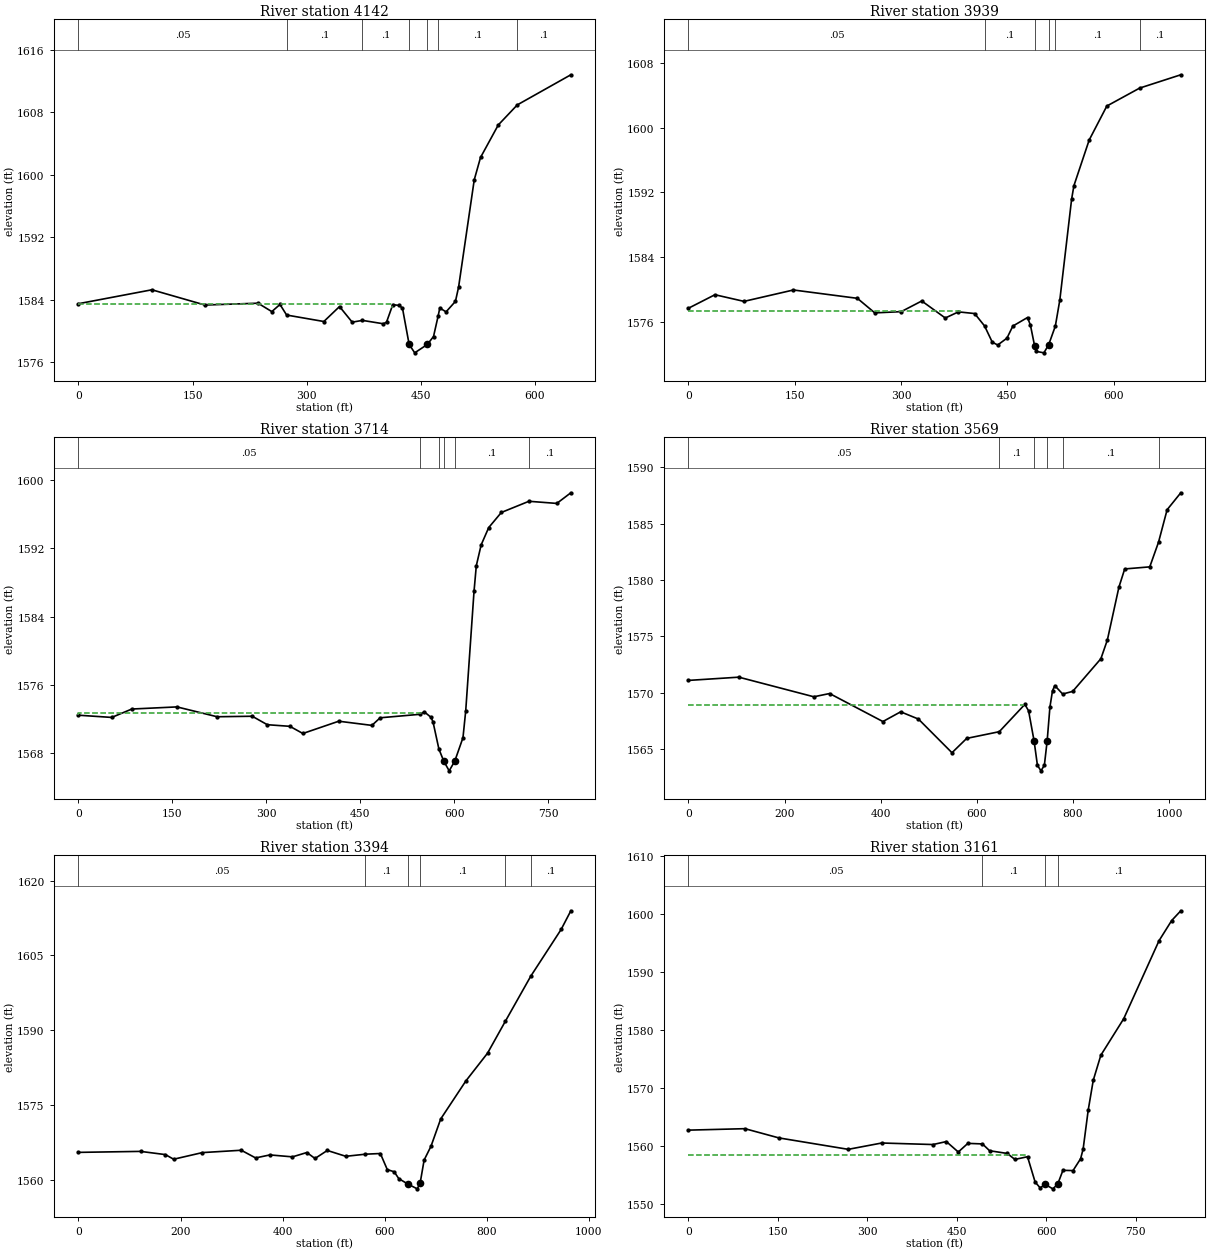
Type RM Length L Ch R = 1 ,4142    ,202.9,202.7,202.3
XS GIS Cut Line= 4
2500660.67587745638469.9542384452500886.37032187638417.870905116
2501181.50921077638344.9542384592501271.78698856638278.982016221
#Sta/Elev= 30
       0 1583.5296.541471585.301166.32861583.349236.13241583.584254.22111582.508
264.97421583.423  273.721582.068 322.6581581.241343.25931583.155359.94871581.156
  373.371581.384400.94311580.951405.06341581.155413.30391583.402421.54441583.297
426.02851582.964   434.81578.313442.14581577.231   458.71578.302466.86741579.318
  473.011581.972475.10791582.973483.34841582.474495.70931583.821499.82951585.647
520.4308 1599.38528.67141602.233552.03231606.397  577.031608.965647.45311612.819
#Mann= 7 ,-1 , 0
       0     .05       0  273.72      .1       0  373.37      .1       0
   434.8    .045       0   458.7      .1       0  473.01      .1       0
  577.03      .1       0
#XS Ineff= 2 , 0
          411.93 1583.49
Permanent Ineff=
       F       F
Bank Sta=434.8,458.7
XS Rating Curve= 0 ,0
Exp/Cntr(USF)=0,0
Exp/Cntr=0.3,0.1

Type RM Length L Ch R = 1 ,3939    ,226.5,225.2,222.8
XS GIS Cut Line= 4
 2500650.2592108638681.7597940122500910.67587748638622.732016236
2501230.12032187638535.9264606832501264.84254411638445.648682892
#Sta/Elev= 30
       01577.69137.411371579.36278.426061578.541 148.1511579.948238.38331578.918
262.99211577.119300.25481577.271329.2702 1578.59362.43061576.487381.02721577.245
403.88121577.037  417.911575.502428.75151573.502436.43631573.151449.4767    1574
457.76681575.491478.49211576.548482.63721575.587   488.61573.001490.92731572.361
501.62341572.184   508.41573.198  517.771575.495524.08771578.719540.73581591.184
543.99511592.843565.53831598.479590.4086 1602.67  636.711604.886694.77621606.531
#Mann= 6 ,-1 , 0
       0     .05       0  417.91      .1       0   488.6    .045       0
   508.4      .1       0  517.77      .1       0  636.71      .1       0
#XS Ineff= 2 , 0
          385.05 1577.31
Permanent Ineff=
       F       F
Bank Sta=488.6,508.4
XS Rating Curve= 0 ,0
Exp/Cntr(USF)=0,0
Exp/Cntr=0.3,0.1

Type RM Length L Ch R = 1 ,3714    ,153.2,145,138.5
XS GIS Cut Line= 4
2500661.71667992638839.809469713 2501011.7291182638858.032942146
2501270.06245151638738.588497713 2501286.7291182638588.588497698
#Sta/Elev= 30
       01572.45553.100191572.19585.143531573.177157.24111573.426221.32771572.275
277.40361572.333301.43611571.343337.48491571.154358.21611570.315415.50541571.752
468.38781571.263481.60851572.153  544.941572.559552.11841572.846563.0588 1572.19
566.07241571.641  575.411568.487   583.21567.071591.78031565.945   600.7 1567.08
613.81461569.824618.22151572.991631.4421 1586.94635.0969 1589.95642.84191592.386
654.91581594.411675.03891596.177  719.121597.487763.58041597.237  786.021598.482
#Mann= 6 ,-1 , 0
       0     .05       0  544.94      .1       0  575.41      .1       0
   583.2    .045       0   600.7      .1       0  719.12      .1       0
#XS Ineff= 2 , 0
          549.79 1572.68
Permanent Ineff=
       F       F
Bank Sta=583.2,600.7
XS Rating Curve= 0 ,0
Exp/Cntr(USF)=0,0
Exp/Cntr=0.3,0.1

Type RM Length L Ch R = 1 ,3569    ,166.3,174.9,178.4
XS GIS Cut Line= 4
2500652.59500539638882.7585007412501214.50689596639013.588497698
2501333.95134041638833.0329421462501317.28467372638602.477386609
#Sta/Elev= 30
       01571.098 104.8821571.386 260.9481569.646 293.8041569.934 404.6921567.449
 441.6551568.312 478.6181567.669 548.4371564.682  579.061565.954  646.861566.549
 700.0771568.973  707.871568.398   719.31565.727 726.2721563.563  733.651563.076
 740.7051563.574   746.51565.732 752.2511568.734  757.631570.185 762.4261570.637
  778.76 1569.89 799.5881570.123 858.2721573.021 871.7761574.682 895.8391579.374
  907.871580.986 960.0061581.171  978.271583.362   996.11586.2391024.5871587.743
#Mann= 6 ,-1 , 0
       0     .05       0  646.86      .1       0   719.3    .045       0
   746.5      .1       0  778.76      .1       0  978.27      .1       0
#XS Ineff= 2 , 0
          698.26 1568.95
Permanent Ineff=
       F       F
Bank Sta=719.3,746.5
XS Rating Curve= 0 ,0
Exp/Cntr(USF)=0,0
Exp/Cntr=0.3,0.1

Type RM Length L Ch R = 1 ,3394    ,228.4,233.4,233.3
XS GIS Cut Line= 4
2500776.97580025639113.2153490742501297.84022933639066.366275474
2501478.39578485638971.9218310422501670.06245154 638830.25516437
#Sta/Elev= 30
       0 1565.47121.68231565.667170.45461565.021186.51921564.093242.74521565.424
 319.0521565.897347.16511564.356375.27811564.958419.4557 1564.57447.56881565.438
463.63341564.244487.73021565.854523.9882 1564.68   562.51565.106591.70081565.241
605.24331562.021618.78581561.571627.8142  1560.2   645.91559.095663.9276 1558.15
   669.61559.257677.47011563.927691.01261566.714709.97141572.175759.17941579.793
801.77671585.382  836.691591.788   886.61600.853946.02361610.218 965.0711613.966
#Mann= 6 ,-1 , 0
       0     .05       0   562.5      .1       0   645.9    .045       0
   669.6      .1       0  836.69     .12       0   886.6      .1       0
Bank Sta=645.9,669.6
XS Rating Curve= 0 ,0
Exp/Cntr(USF)=0,0
Exp/Cntr=0.3,0.1

Type RM Length L Ch R = 1 ,3161    ,197.7,199,197.5
XS GIS Cut Line= 4
2500775.51850078639227.2037442792501272.84022933639263.588497713
2501431.17356265639208.0329421462501581.17356262 639155.25516437
#Sta/Elev= 30
       01562.751 94.70191563.002151.63071561.411267.9408 1559.44324.09041560.532
410.08441560.267432.3791 1560.78452.43261558.979468.47531560.469  492.931560.373
504.90871559.199534.58231558.731547.2995  1557.7568.49491558.167581.21221553.813
589.69041552.792     5981553.408610.88581552.629     6191553.415627.84211555.818
644.79851555.776657.51571557.825661.75481559.504670.23411566.195678.71491571.354
 691.4361575.669729.74191581.955788.9647 1595.41810.16661598.889825.46221600.572
#Mann= 4 ,-1 , 0
       0     .05       0  492.93      .1       0     598    .045       0
     619      .1       0
#XS Ineff= 2 , 0
          566.53 1558.41
Permanent Ineff=
       F       F
Bank Sta=598,619
XS Rating Curve= 0 ,0
Exp/Cntr(USF)=0,0
Exp/Cntr=0.3,0.1