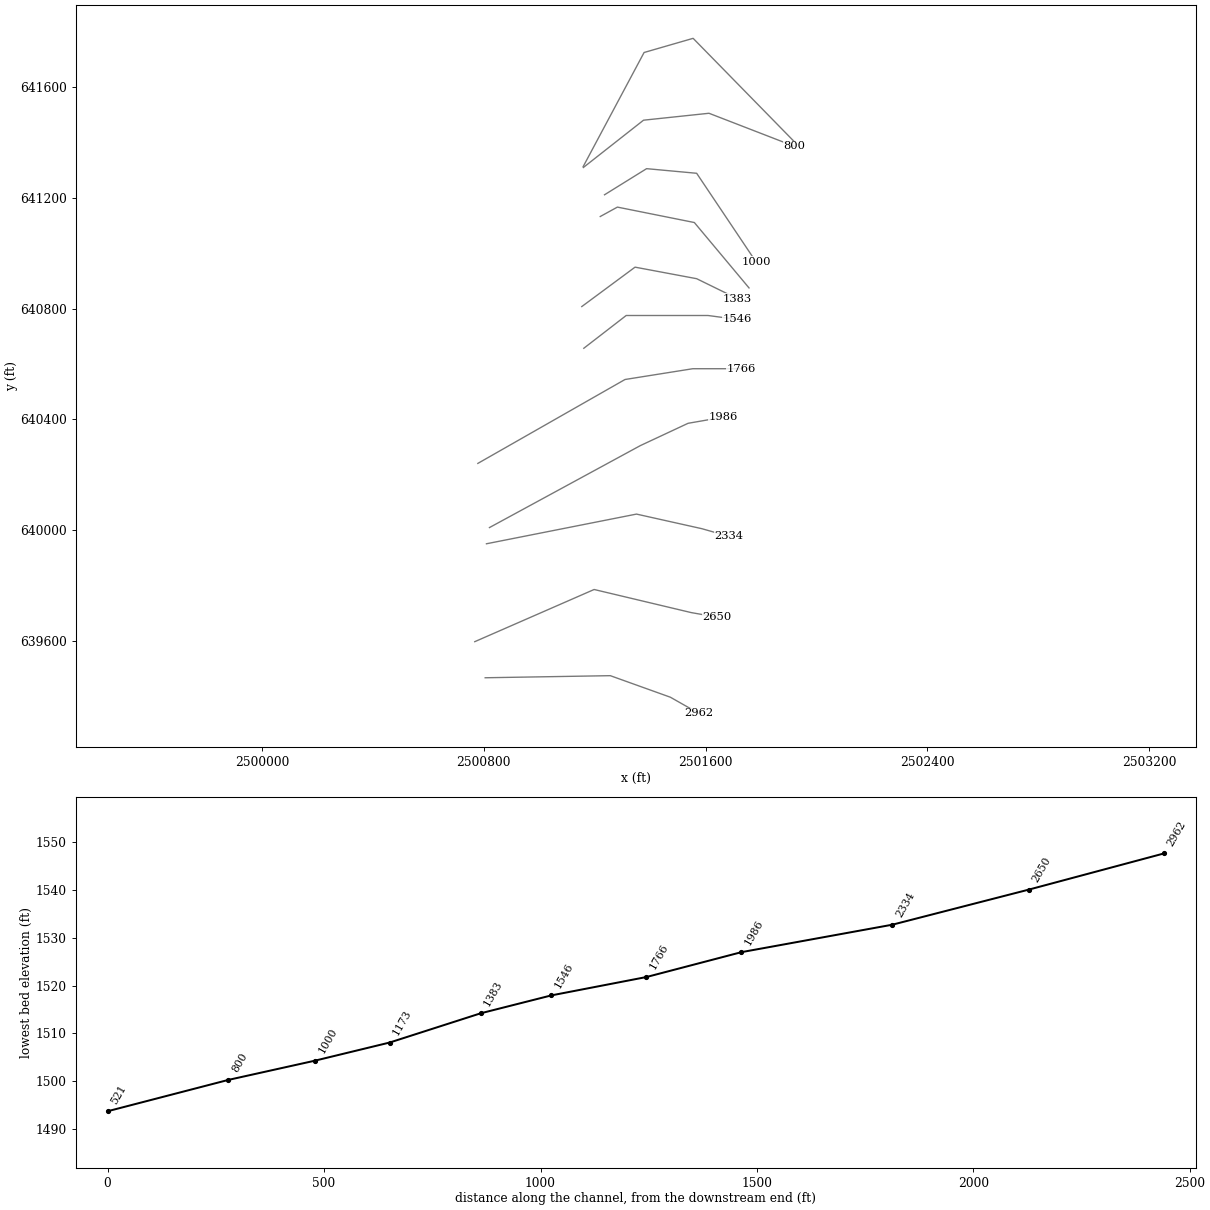
HEC-RAS study BUCKLICKRN.prj: BUCKLICKRN

--- BUCKLICKRN.g01 (geometry) --- (continued)

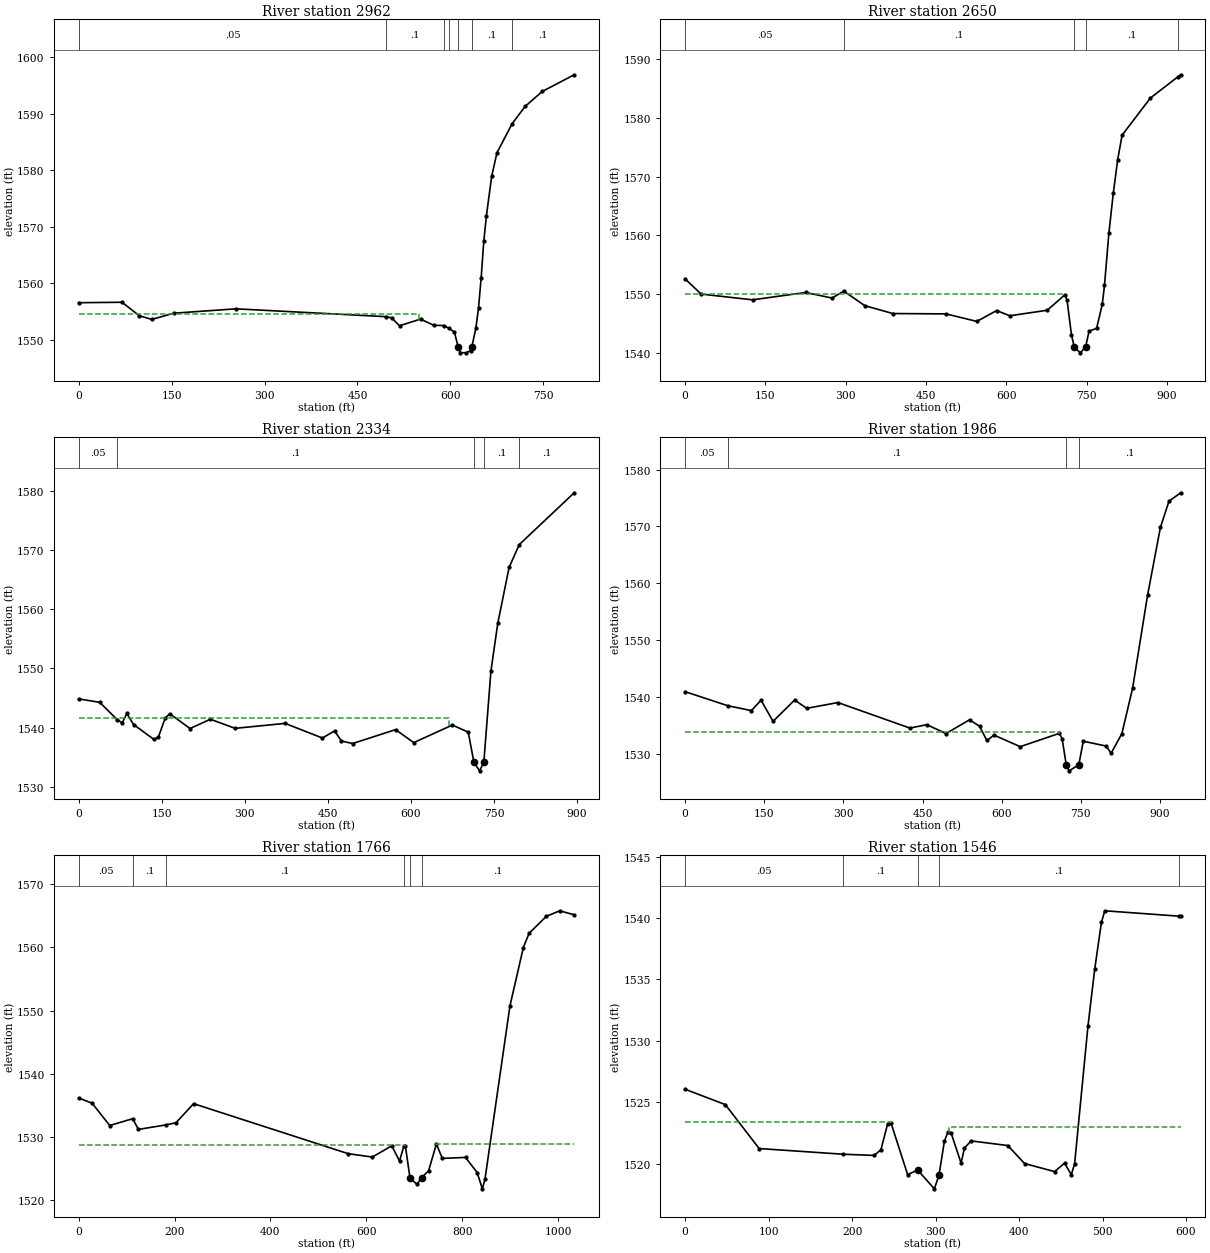
Type RM Length L Ch R = 1 ,2962    ,311.4,311.9,313.5
XS GIS Cut Line= 4
2500804.83382516639467.1775834862501256.17356265639474.699608818
2501472.84022933639396.9218310422501575.61800709639338.588497713
#Sta/Elev= 30
       0 1556.5469.920921556.61997.924811554.239117.92761553.586153.93261554.683
253.94651555.457  496.841554.063505.13361553.857517.88331552.458551.88271553.635
573.13231552.541  589.021552.498  597.861551.997606.50091551.346   612.61548.663
615.88281547.712625.26471547.665632.63111548.058   634.6  1548.7641.13091552.044
645.38091555.578649.63081560.894653.88071567.382658.13061571.927666.63041578.906
675.13031583.078  699.721588.242720.59141591.282748.1876 1593.93799.78441596.889
#Mann= 7 ,-1 , 0
       0     .05       0  496.84      .1       0  589.02     .05       0
  597.86      .1       0   612.6    .045       0   634.6      .1       0
  699.72      .1       0
#XS Ineff= 2 , 0
          549.79 1554.61
Permanent Ineff=
       F       F
Bank Sta=612.6,634.6
XS Rating Curve= 0 ,0
Exp/Cntr(USF)=0,0
Exp/Cntr=0.3,0.1

Type RM Length L Ch R = 1 ,2650    ,314.2,315.8,316.1
XS GIS Cut Line= 4
2500767.28467372639597.4382304252501197.84022933639785.810719937
 2501547.8402293639702.4773865942501642.28467375639685.810719937
#Sta/Elev= 30
       01552.64429.973531550.065126.02731549.092225.44981550.335274.47391549.389
  296.311550.563335.59911548.108 387.9921546.766487.33721546.705544.90261545.432
 581.9091547.266606.57991546.386676.48081547.327709.37531549.931713.48711549.036
721.71081543.156     7271541.061 738.158  1540.1     7481541.071754.60531543.764
768.71171544.264779.27621548.338 783.3881551.522791.61161560.419799.83531567.165
808.05891572.851816.28251577.011869.24971583.324  920.911586.942925.64751587.257
#Mann= 5 ,-1 , 0
       0     .05       0  296.31      .1       0     727    .045       0
     748      .1       0  920.91     .12       0
#XS Ineff= 2 , 0
           703.7 1550.15
Permanent Ineff=
       F       F
Bank Sta=727,748
XS Rating Curve= 0 ,0
Exp/Cntr(USF)=0,0
Exp/Cntr=0.3,0.1

Type RM Length L Ch R = 1 ,2334    ,341,348.6,356.2
XS GIS Cut Line= 4
2500809.45529727639950.8796556842501350.61800709640058.032942146
2501586.72911817 640005.255164372501683.95134044639977.477386609
#Sta/Elev= 30
       01544.87638.013711544.289   69.631541.375 78.79031540.81386.945611542.428
99.178591540.551135.87751538.038144.03281538.442156.26581541.619164.42111542.376
201.12011539.873 237.8191541.435282.67321539.906372.78621540.736440.18511538.272
462.09021539.473474.47421537.776494.71151537.342572.29291539.688605.08261537.496
674.7607 1540.46703.45171539.264   713.71534.176723.94531532.738   731.61534.173
744.43881549.588 756.7351557.586777.22861567.035  795.531570.884894.71971579.625
#Mann= 5 ,-1 , 0
       0     .05       0   69.63      .1       0   713.7    .045       0
   731.6      .1       0  795.53      .1       0
#XS Ineff= 2 , 0
          669.41 1541.72
Permanent Ineff=
       F       F
Bank Sta=713.7,731.6
XS Rating Curve= 0 ,0
Exp/Cntr(USF)=0,0
Exp/Cntr=0.3,0.1

Type RM Length L Ch R = 1 ,1986    ,222.2,219.5,214.7
XS GIS Cut Line= 4
2500820.29597239 640009.385122122501364.50689596640305.255164385
2501536.72911817640385.8107199222501664.50689599640408.032942146
#Sta/Elev= 30
       0 1540.92   80.84 1538.45125.71681537.585143.9285 1539.42166.6932  1535.7
207.66961539.451230.43421537.987289.62241539.006426.21041534.513458.08091535.115
494.50441533.552539.11881535.969558.24541534.826571.90421532.331 585.5631533.273
635.15771531.244709.60391533.592714.64451532.645   722.51528.012727.8924 1526.99
   746.21528.054754.73381532.203798.54741531.338807.37931530.063 827.856 1533.53
848.1563  1541.5876.57651557.887900.93681569.826917.17691574.427939.26541575.916
#Mann= 4 ,-1 , 0
       0     .05       0   80.84      .1       0   722.5    .045       0
   746.2      .1       0
#XS Ineff= 2 , 0
          707.82 1533.84
Permanent Ineff=
       F       F
Bank Sta=722.5,746.2
XS Rating Curve= 0 ,0
Exp/Cntr(USF)=0,0
Exp/Cntr=0.3,0.1

Type RM Length L Ch R = 1 ,1766    ,221.1,219.6,217.1
XS GIS Cut Line= 4
2500778.39741637640241.0213996922501309.32171077640543.958868086
2501553.76615524640582.8477569672501728.76615524640582.847756967
#Sta/Elev= 30
       01536.15728.032221535.34264.874871531.804  112.78 1532.88124.74421531.188
  182.961531.908203.0348 1532.24239.87751535.258562.25071527.346612.71181526.814
653.21481528.594669.41611526.182  678.671528.593 681.5671528.617   691.31523.478
705.86881522.502   715.41523.535730.17061524.664746.37181528.875758.7678  1526.6
807.12641526.755831.42821524.353  842.211521.781847.62941523.261 899.7681550.724
 927.7681559.973 939.7681562.222 975.7681564.9091003.7681565.7851033.7891565.146
#Mann= 6 ,-1 , 0
       0     .05       0  112.78      .1       0  182.96      .1       0
  678.67      .1       0   691.3    .045       0   715.4      .1       0
#XS Ineff= 2 , 0
          679.84 1528.76  745.68         1528.95
Permanent Ineff=
       F       F
Bank Sta=691.3,715.4
XS Rating Curve= 0 ,0
Exp/Cntr(USF)=0,0
Exp/Cntr=0.3,0.1

Type RM Length L Ch R = 1 ,1546    ,165.3,163.4,161.4
XS GIS Cut Line= 4
2501160.62185319640656.6997238892501313.48837748640774.977386609
2501608.62726635640774.977386609  2501712.793933640761.088497698
#Sta/Elev= 30
       01526.04948.202251524.79788.662461521.219  189.691520.754226.53831520.658
234.53831521.126242.53831523.213246.53831523.314266.53831519.096   278.61519.462
298.53831517.936   304.11519.051310.53831521.808314.62481522.529318.53831522.501
330.53831520.035334.53831521.255342.53831521.841386.53831521.463406.53831519.999
442.5383 1519.34454.53831520.031462.53831519.084466.53831519.989482.53831531.209
 490.5571535.806498.62781539.645502.66321540.587  591.941540.146 593.5091540.137
#Mann= 5 ,-1 , 0
       0     .05       0  189.69      .1       0   278.6    .045       0
   304.1      .1       0  591.94    .055       0
#XS Ineff= 2 , 0
          246.09 1523.41  316.05         1522.97
Permanent Ineff=
       F       F
Bank Sta=278.6,304.1
XS Rating Curve= 0 ,0
Exp/Cntr(USF)=0,0
Exp/Cntr=0.3,0.1

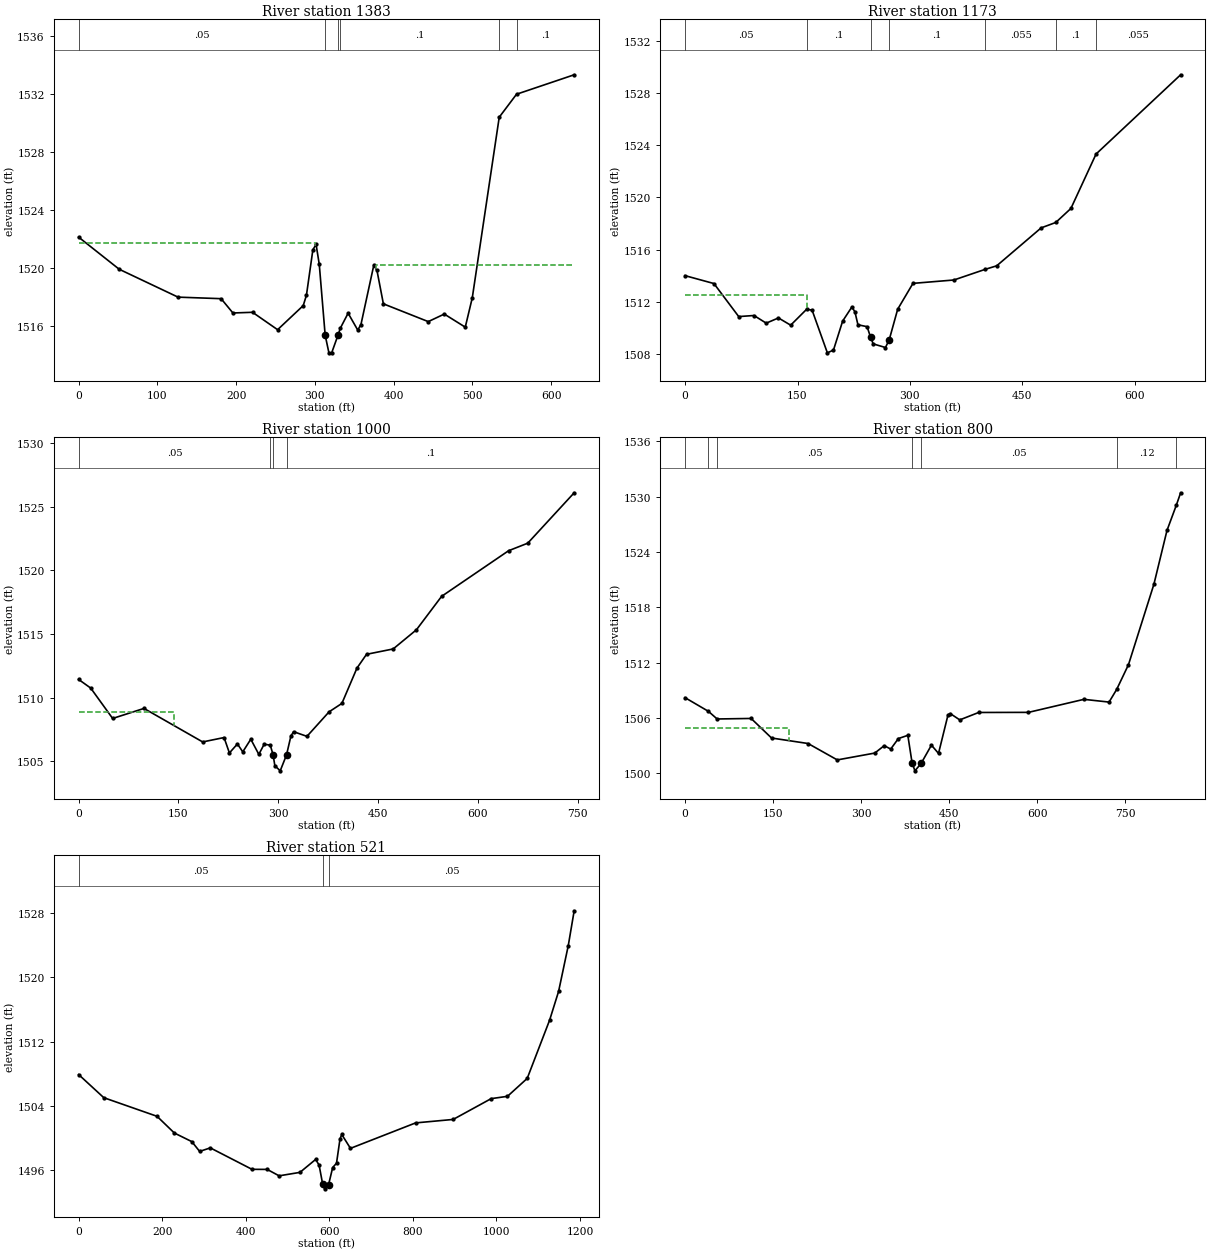
Type RM Length L Ch R = 1 ,1383    ,210,210.2,209.3
XS GIS Cut Line= 4
2501153.31503635 640807.22713866 2501345.4328219640949.514423624
2501567.65504411640907.8477569672501714.87726632640835.625534743
#Sta/Elev= 30
       01522.138 51.55541519.929126.21931518.013180.89651517.907195.90551516.923
220.79351516.971252.61511515.774285.17281517.432289.24251518.147297.38191521.263
301.45161521.644305.52131520.268     3131515.399317.73041514.192321.26681514.183
   329.41515.411  332.361515.888342.14871516.909354.35781515.749358.42751516.127
374.70631520.198 378.7761519.848386.91541517.553443.8913 1516.33464.23981516.849
490.88441515.949499.79521517.969  534.011530.386  555.951531.964629.14871533.302
#Mann= 6 ,-1 , 0
       0     .05       0     313    .045       0   329.4     .05       0
  332.36      .1       0  534.01    .055       0  555.95      .1       0
#XS Ineff= 2 , 0
          300.55 1521.72  377.37         1520.19
Permanent Ineff=
       F       F
Bank Sta=313,329.4
XS Rating Curve= 0 ,0
Exp/Cntr(USF)=0,0
Exp/Cntr=0.3,0.1

Type RM Length L Ch R = 1 ,1173    ,171.4,172.9,173.3
XS GIS Cut Line= 4
2501219.93590687641132.357684517 2501281.7717033641166.314256713
 2501559.3217108641110.625534758  2501756.543933640874.514423624
#Sta/Elev= 30
       01513.99138.503281513.38571.538571510.84991.937181510.931108.25611510.344
 124.5751510.744140.89381510.188  162.091511.405169.45191511.346189.85051508.064
198.00991508.278210.24911510.503222.4883 1511.58 226.5681511.227230.64771510.219
242.88691510.074   247.61509.244251.04631508.751267.36521508.473   272.41509.068
283.68411511.414304.08271513.399358.70931513.658  400.64 1514.48415.82411514.747
475.14091517.661  494.631518.075514.84941519.153  548.421523.333661.27191529.418
#Mann= 7 ,-1 , 0
       0     .05       0  162.09      .1       0   247.6    .045       0
   272.4      .1       0  400.64    .055       0  494.63      .1       0
  548.42    .055       0
#XS Ineff= 2 , 0
          162.28 1512.52
Permanent Ineff=
       F       F
Bank Sta=247.6,272.4
XS Rating Curve= 0 ,0
Exp/Cntr(USF)=0,0
Exp/Cntr=0.3,0.1

Type RM Length L Ch R = 1 ,1000    ,197.7,199.7,202
XS GIS Cut Line= 4
 2501235.3476518641210.8087193052501387.09948859641305.069979206
2501567.65504411641288.403312519  2501781.543933640968.958868086
#Sta/Elev= 30
       01511.43118.126021510.75551.08801 1508.3798.176551509.158186.32241506.528
218.45851506.872226.49251505.663238.5435 1506.37246.5775 1505.75258.62851506.741
270.67951505.554278.71351506.347  287.931506.277   292.11505.514294.78161504.664
302.8156 1504.26   312.31505.511318.88361506.993322.90061507.332342.98561506.966
376.2292 1508.89395.48461509.552418.06761512.319 432.4841513.404 472.5061513.825
507.44961515.329 545.2591517.952645.91211521.533674.68741522.125744.4063 1526.08
#Mann= 4 ,-1 , 0
       0     .05       0  287.93      .1       0   292.1    .045       0
   312.3      .1       0
#XS Ineff= 2 , 0
          143.76 1508.86
Permanent Ineff=
       F       F
Bank Sta=292.1,312.3
XS Rating Curve= 0 ,0
Exp/Cntr(USF)=0,0
Exp/Cntr=0.3,0.1

Type RM Length L Ch R = 1 ,800     ,277,278.9,280.3
XS GIS Cut Line= 4
2501159.00798035641309.3316594242501375.98837745641480.069979191
2501612.09948856641505.0699791912501920.43282187641385.625534743
#Sta/Elev= 30
       0 1508.18   39.771506.698   54.56 1505.87112.48451505.927147.27221503.804
209.51071503.206259.24981501.426323.11961502.169 339.2091502.973350.28091502.605
363.34321503.744379.43261504.095   386.6 1501.14391.4997 1500.24     4021501.038
419.65621503.027431.72331502.133447.81271506.293451.83511506.452467.92451505.771
500.10341506.576 585.0041506.588679.37631508.001722.27291507.704  735.231509.077
755.33751511.766798.62391520.489820.93481526.337  836.751529.059844.19311530.425
#Mann= 7 ,-1 , 0
       0     .05       0   39.77      .1       0   54.56     .05       0
   386.6    .045       0     402     .05       0  735.23     .12       0
  836.75      .1       0
#XS Ineff= 2 , 0
          176.95 1504.84
Permanent Ineff=
       F       F
Bank Sta=386.6,402
XS Rating Curve= 0 ,0
Exp/Cntr(USF)=0,0
Exp/Cntr=0.3,0.1

Type RM Length L Ch R = 1 ,521     ,267,272.4,275.7
XS GIS Cut Line= 4
2501158.42526517641312.7370667182501378.03372524641724.456958287
2501554.90328298641775.5833148182501929.36929973641392.826537542
#Sta/Elev= 30
       0 1507.91    60.2 1505.03   187.7 1502.71   229.1 1500.63   270.9 1499.56
   289.7 1498.34   315.2 1498.78     415 1496.11   451.3  1496.1   479.9  1495.3
   529.8 1495.73   567.3 1497.34   575.6 1496.64     584 1494.31   588.7 1493.68
   598.4 1494.22   608.1 1496.33   617.3 1496.87   625.6 1499.87   629.8 1500.45
   650.7 1498.72   806.7 1501.89   896.5 1502.32   987.5 1504.91  1026.6  1505.2
  1073.8 1507.43  1127.4 1514.68  1148.9 1518.26  1172.1 1523.97  1186.2  1528.3
#Mann= 3 , 0 , 0
       0     .05       0     584    .045       0   598.4     .05       0
Bank Sta=584,598.4
XS Rating Curve= 0 ,0
Exp/Cntr(USF)=0,0
Exp/Cntr=0.3,0.1