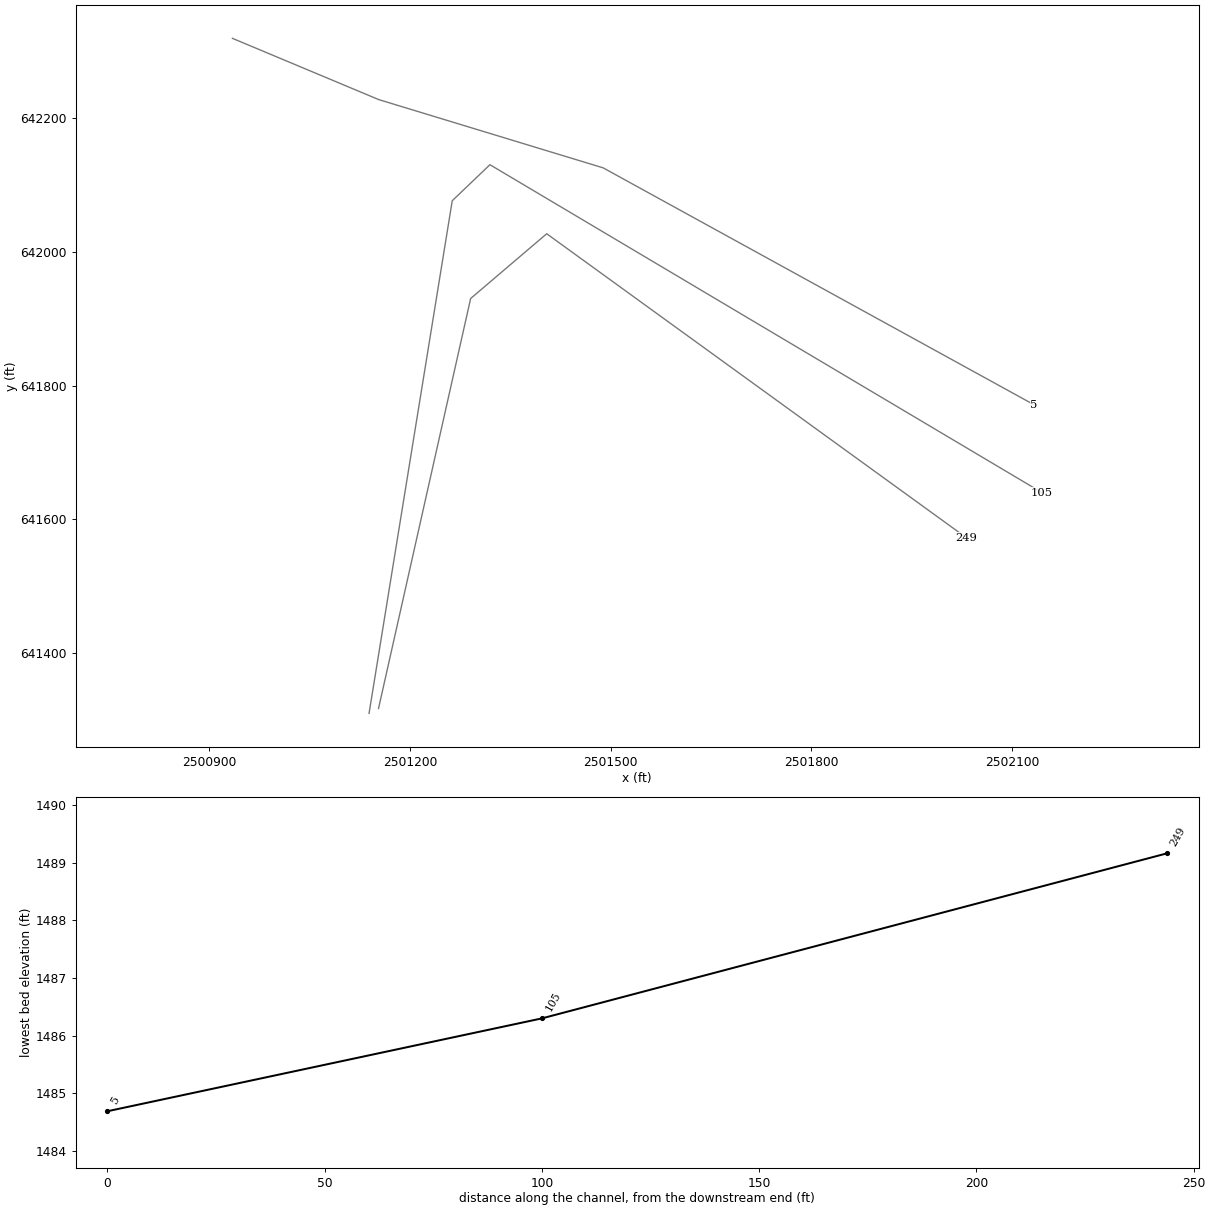
HEC-RAS study BUCKLICKRN.prj: BUCKLICKRN

--- BUCKLICKRN.g01 (geometry) --- (continued)

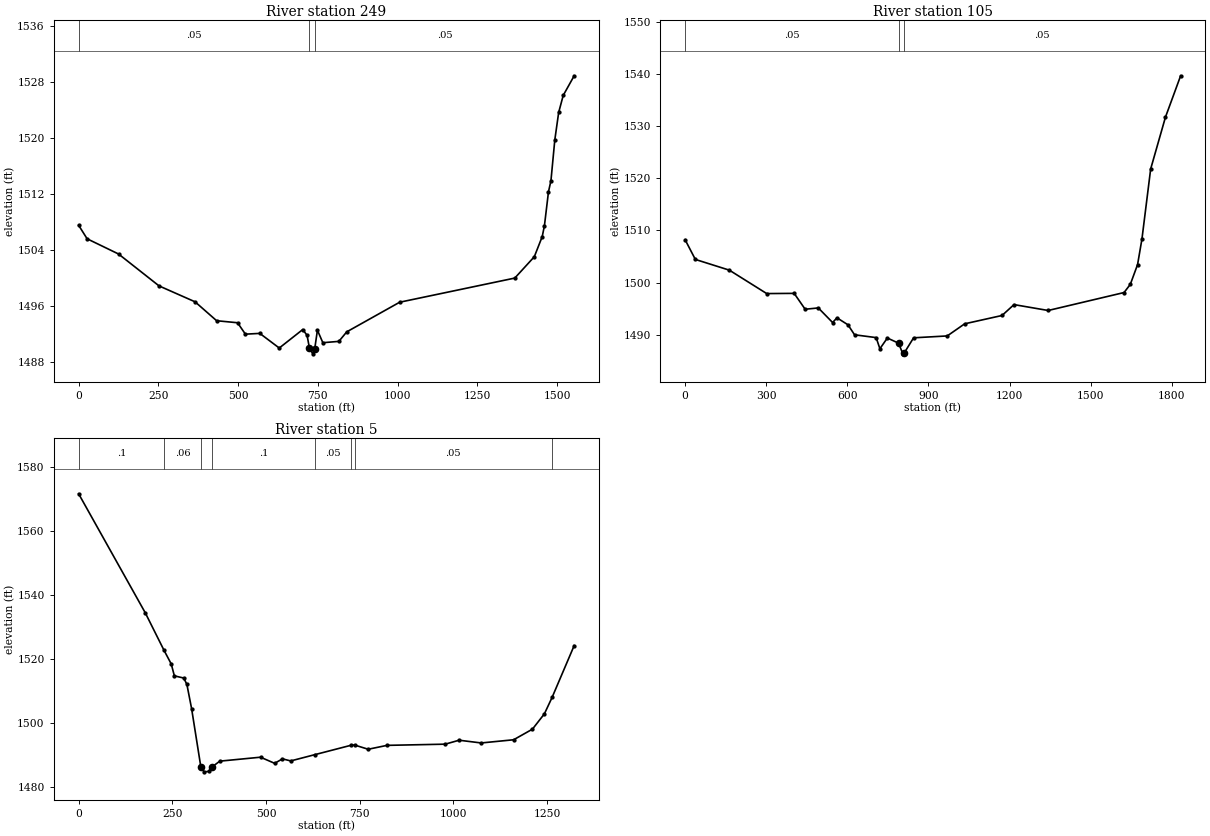
Type RM Length L Ch R = 1 ,249     ,140.8,143.8,149.8
XS GIS Cut Line= 4
2501152.83933812641316.9081686942501290.54516285641930.201928508
2501404.27301633642027.0812111012502031.88228183641572.169797185
#Sta/Elev= 30
       0 1507.52    26.6 1505.59     125 1503.42   252.1 1498.86   364.9 1496.59
   432.5 1493.89   498.1  1493.6   522.7 1491.97   567.8 1492.08   628.8 1489.99
   702.4 1492.63     716  1491.8   723.4 1489.97   733.9 1489.16   739.9 1489.86
   748.4 1492.54   765.4 1490.75   815.6 1490.94   840.3  1492.3  1006.1 1496.53
    1367 1499.98  1428.2 1503.03    1453 1505.91  1459.9 1507.46  1472.6 1512.31
  1480.3 1513.88  1492.4 1519.71  1504.5 1523.63  1518.8 1526.07  1553.1 1528.87
#Mann= 3 , 0 , 0
       0     .05       0   723.4    .045       0   739.9     .05       0
Bank Sta=723.4,739.9
XS Rating Curve= 0 ,0
Exp/Cntr(USF)=0,0
Exp/Cntr=0.3,0.1

Type RM Length L Ch R = 1 ,105     ,100,100,100
XS GIS Cut Line= 4
2501138.69954908641309.6018307482501263.04557115642076.454964983
2501319.37193709642130.3669564492502144.34730341641639.977085782
#Sta/Elev= 30
       0 1508.23    37.9 1504.44   163.6 1502.38   301.8 1497.88   403.3 1497.92
   443.9 1494.87   492.6 1495.12   545.4 1492.32   561.6 1493.22   602.2 1491.88
   626.6 1489.96   706.4 1489.42   720.3 1487.28   747.9 1489.34   789.41488.349
   805.1  1486.3   809.3 1486.39   844.9 1489.38   969.3 1489.74  1033.8 1492.07
  1171.9 1493.67  1216.2 1495.76  1342.5 1494.63  1623.2 1498.08  1646.3 1499.66
  1673.1 1503.45  1689.3 1508.38  1721.5 1521.82  1776.2 1531.781832.336 1539.73
#Mann= 3 , 0 , 0
       0     .05       0   789.4    .045       0   809.3     .05       0
Bank Sta=789.4,809.3
XS Rating Curve= 0 ,0
Exp/Cntr(USF)=0,0
Exp/Cntr=0.3,0.1

Type RM Length L Ch R = 1 ,5       ,5,5,5
XS GIS Cut Line= 4
2500934.46440259642319.4028991612501153.21440259642227.736232489
2501488.63106927642125.6528991612502132.38106924641771.486232504
#Sta/Elev= 30
       01571.515177.86981534.344  227.911522.632247.14221518.382255.50451514.661
280.59151513.977288.95381511.971301.49721504.432   326.2  1486.2334.9464 1484.69
347.48991484.821   355.81486.196 376.7581488.028 485.468 1489.26523.0983 1487.35
544.00411488.742566.05021488.098  631.111490.078  727.711493.006  736.541493.057
772.81571491.744823.03511492.957978.2586 1493.331015.4731494.5631074.3751493.709
1160.8751494.7031211.0941498.0121243.0521502.799 1263.691507.9551322.5311524.112
#Mann= 8 ,-1 , 0
       0      .1       0  227.91     .06       0   326.2    .045       0
   355.8      .1       0  631.11     .05       0  727.71      .1       0
  736.54     .05       0 1263.69      .1       0
Bank Sta=326.2,355.8
XS Rating Curve= 0 ,0
Exp/Cntr(USF)=0,0
Exp/Cntr=0.3,0.1
LCMann Table=0

Chan Stop Cuts=-1
Use User Specified Reach Order=0
Composite Channel Slope=5